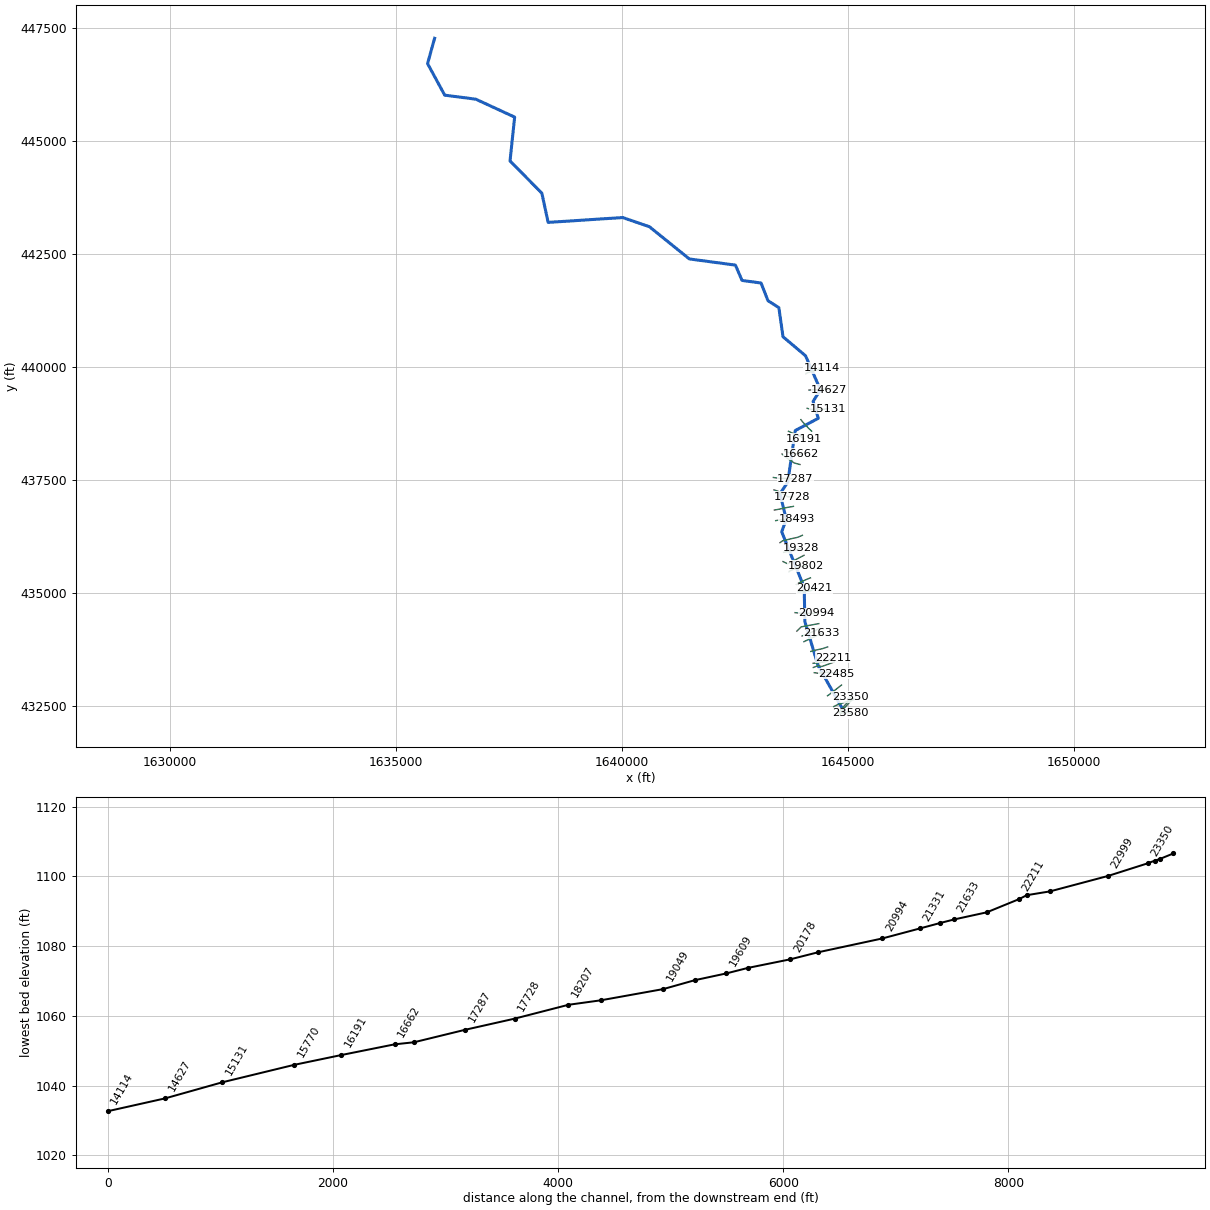
--- LYNNCMPRN.prj (project) ---

Proj Title=LYNNCMPRN
Current Plan=p01
Default Exp/Contr=0,0
English Units
Geom File=g01
Flow File=f01
Plan File=p01
BEGIN DESCRIPTION:
---------- MODELED AS PART OF WVEMD CTP PROGRAM, 2023----------
Stream Name: Lynn Camp Run
Flood Zone:  AFH
Wetzel County, WV
HEC-RAS Version: RAS 6.3
Vertical Datum: NAVD88
Projection: NAD 1983 StatePlane West Virginia S FIPS 4702 (US Feet)
Terrain: 1-meter West Virginia FEMA R3 South Central (collected 2018-2020)
Land Use: 2019 NLCD
Hydrologic Method:
WV SIR2010-5033 regression equations
Additional Model Notes:
DS end is out of Wetzel County
END DESCRIPTION:
DSS File=dss
DSS Export Rating Curves= 0
DSS Export Rating Curve Sorted= 0
DSS Export Volume Flow Curves= 0
DXF OffsetX= 0
DXF OffsetY= 0
DXF ScaleX= 0
DXF ScaleY= 0

--- LYNNCMPRN.p01 (plan) ---

Plan Title=Floodplain
Program Version=6.31
Short Identifier=Floodplain
Geom File=g01
Flow File=f01
Subcritical Flow
K Sum by GR= 0
Std Step Tol= 0.01
Critical Tol= 0.01
Num of Std Step Trials= 20
Max Error Tol= 0.3
Flow Tol Ratio= 0.001
Split Flow NTrial= 30
Split Flow Tol= 0.02
Split Flow Ratio= 0.02
Log Output Level= 0
Friction Slope Method= 1
Unsteady Friction Slope Method= 2
Unsteady Bridges Friction Slope Method= 1
Parabolic Critical Depth
Global Vel Dist= 0 , 0 , 0
Global Log Level= 0
CheckData=False
Encroach Param=-1 ,0,0, 0
Computation Interval=0.1SEC
Output Interval=1SEC
Instantaneous Interval=Max Profile
Mapping Interval=1HOUR
Computation Time Step Use Courant=        0
Computation Time Step Use Time Series=    0
Computation Time Step Count To Double=0
Computation Time Step Max Doubling=0
Computation Time Step Max Halving=0
Computation Time Step Residence Courant=0
Run HTab= 0
Run UNet= 0
Run Sediment= 0
Run PostProcess= 0
Run WQNet= 0
Run RASMapper=-1
UNET Theta= 0
UNET Theta Warmup= 0
UNET ZTol= 0
UNET ZSATol= 0
UNET MxIter= 0
UNET Max Iter WO Improvement= 0
UNET MaxInSteps= 0
UNET DtIC= 0
UNET DtMin= 0
UNET MaxCRTS= 0
UNET WFStab= 0
UNET SFStab= 0
UNET WFX= 1
UNET SFX= 1
UNET Gravity=32.17405
UNET 1D Methodology=Finite Difference
UNET DSS MLevel= 1
UNET Pardiso=0
UNET DZMax Abort= 0
UNET Use Existing IB Tables= 0
UNET Froude Reduction=False
UNET Froude Limit= 0
UNET Froude Power= 0
UNET D1 Cores= 0
UNET WindReference=Eulerian
UNET WindDragFormulation=Hsu (1988)
UNET D2 Coriolis=0
UNET D2 Cores= 0
UNET D2 Theta= 1
UNET D2 Theta Warmup= 1
UNET D2 Z Tol= 0.01
UNET D2 Volume Tol= 0.01
UNET D2 Max Iterations= 20
UNET D2 Equation= 0
UNET D2 RampUpFraction=0.1
UNET D2 TimeSlices= 1
UNET D2 Turbulence Formulation=Non-Conservative (original)
UNET D2 Eddy Viscosity=0.3
UNET D2 Transverse Eddy Viscosity=0.1
UNET D2 Smagorinsky Mixing=0
UNET D2 BCVolumeCheck=0
UNET D2 Cores=0
UNET D2 SolverType=PARDISO (Direct)
UNET D2 Minimum Iterations= 3
UNET D2 Maximum Iterations= 30
UNET D2 Restart Number= 10
UNET D2 Relaxation Coeff=1.3
UNET D2 SOR Precondition Iterations= 10
UNET D2 ILUT Maximum Fill= 8
UNET D2 ILUT Tolerance=1E-08
UNET D2 Convergence Tolerance=0.00001
UNET D1D2 MaxIter= 0
UNET D1D2 ZTol=0.01
UNET D1D2 QTol=0.1
UNET D1D2 MinQTol=1
DSS File=dss
Write IC File= 0
Write IC File at Fixed DateTime=0
Write IC File at Sim End=0
Echo Input=False
Echo Parameters=False
Echo Output=False
Write Detailed= 0
HDF Write Warmup=0
HDF Write Time Slices=0
HDF Flush=0
HDF Compression= 1
HDF Chunk Size= 1
HDF Spatial Parts= 1
HDF Use Max Rows=0
HDF Fixed Rows= 1
Calibration Method= 0
Calibration Iterations= 20
Calibration Max Change=0.05
Calibration Tolerance=0.2
Calibration Maximum=1.5
Calibration Minimum=0.5
Calibration Optimization Method= 1
WQ AD Non Conservative
WQ ULTIMATE=-1
WQ Max Comp Step=1HOUR
WQ Output Interval=15MIN
WQ Output Selected Increments= 0
WQ Create Restart=0
WQ Fixed Restart=0
WQ System Summary=0
WQ Write To DSS=0
Sorting and Armoring Iterations= 10
XS Update Threshold= 0.02
Bed Roughness Predictor= 0
Hydraulics Update Threshold= 0.02
Energy Slope Method= 1
Volume Change Method= 1
Sediment Retention Method= 0
Sediment TS Multiplier= 1
Warm Up Method= 0
XS Weighting Method= 0
Number of US Weighted Cross Sections= 1
Number of DS Weighted Cross Sections= 1
Upstream XS Weight=0
Main XS Weight=1
Downstream XS Weight=0
Number of DS XS's Weighted with US Boundary= 1
Upstream Boundary Weight= 1
Weight of XSs Associated with US Boundary= 0
Number of US XS's Weighted with DS Boundary= 1
Downstream Boundary Weight= 0.5
Weight of XSs Associated with DS Boundary= 0.5
Percentile Method= 0
Sediment Output Level= 3
Mass or Volume Output= 0
Output Increment Type= 1
Profile and TS Output Increment= 1
Transport Output Increment 1
XS Output Flag= 0
XS Output Increment= 10
Read HDF5 Sediment Hotstart= 0
Sediment Hotstart Type= 0
Write Gradation File= 0
Read Gradation Hotstart= 0
Write HDF5 File= 1
Write Binary Output= 1
Write DSS Sediment File= 0
DSS Sediment Output Type= 1
SV Curve= 0
Specific Gage Flag= 0
Subcell Erosion Methods= 0
Subcell Deposition Methods= 0
Advection Scheme= 1
Matrix Solver= 0
Implicit Weighting Factor= 1
Maximum Outer Loop Convergence Iterations= 5
Convergence Maximum Absolute= 0.001
Convergence RMSE= 0.0001
Grain Fractions Max Abs Error= 0.001
Max Subgrid Regions= 1
Max Subgrid Length Scale= 3.402823E+38
Initial Layer Thickness= 3.402823E+38
Min Layer Thickness= 3.402823E+38
Max Layer Thickness= 3.402823E+38
Number of Layers= 5

--- LYNNCMPRN.f01 (steady flow) ---

Flow Title=Flow
Program Version=6.30
Number of Profiles= 1
Profile Names=F01pct
River Rch & RM=LYNNCMPRN,Main,23580
     786
River Rch & RM=LYNNCMPRN,Main,19609
     921
River Rch & RM=LYNNCMPRN,Main,16662
    1030
River Rch & RM=LYNNCMPRN,Main,14627
    1150
River Rch & RM=LYNNCMPRN,Main,12208
    1310
River Rch & RM=LYNNCMPRN,Main,9737
    1460
River Rch & RM=LYNNCMPRN,Main,6500
    2350
River Rch & RM=LYNNCMPRN,Main,1758
    3060
Boundary for River Rch & Prof#=LYNNCMPRN,Main            , 1
Up Type= 0
Dn Type= 3
Dn Slope=0.005
DSS Import GetInterval= 0
DSS Import GetPeak= 0
DSS Import FillOption= 0

--- LYNNCMPRN.g01 (geometry) ---

Geom Title=Geometry
Program Version=6.31

River Reach=LYNNCMPRN       ,Main
Reach XY= 30
1644928.00102109 432344.42905765     1644334.959      433396.934
     1644045.018      434364.711     1644029.781      435122.215
     1643532.179      436351.636     1643633.615      436626.776
     1643494.304      437192.727     1643666.266      437448.276
     1643832.569      438591.062     1644341.489      438860.978
     1644227.429      439233.635     1644387.201      439493.537
      1644059.82      440244.076     1643561.783      440664.622
     1643469.924      441307.629     1643229.177      441462.613
     1643075.935       441853.12     1642654.954      441911.021
     1642508.677      442249.286     1641489.965      442385.985
      1640606.21      443098.648      1640016.75       443301.52
     1638366.754      443194.018     1638228.065      443839.696
     1637523.951      444553.822     1637626.084      445522.679
     1636766.969      445919.193     1636079.678      446008.109
     1635700.386      446705.814     1635855.387      447264.939

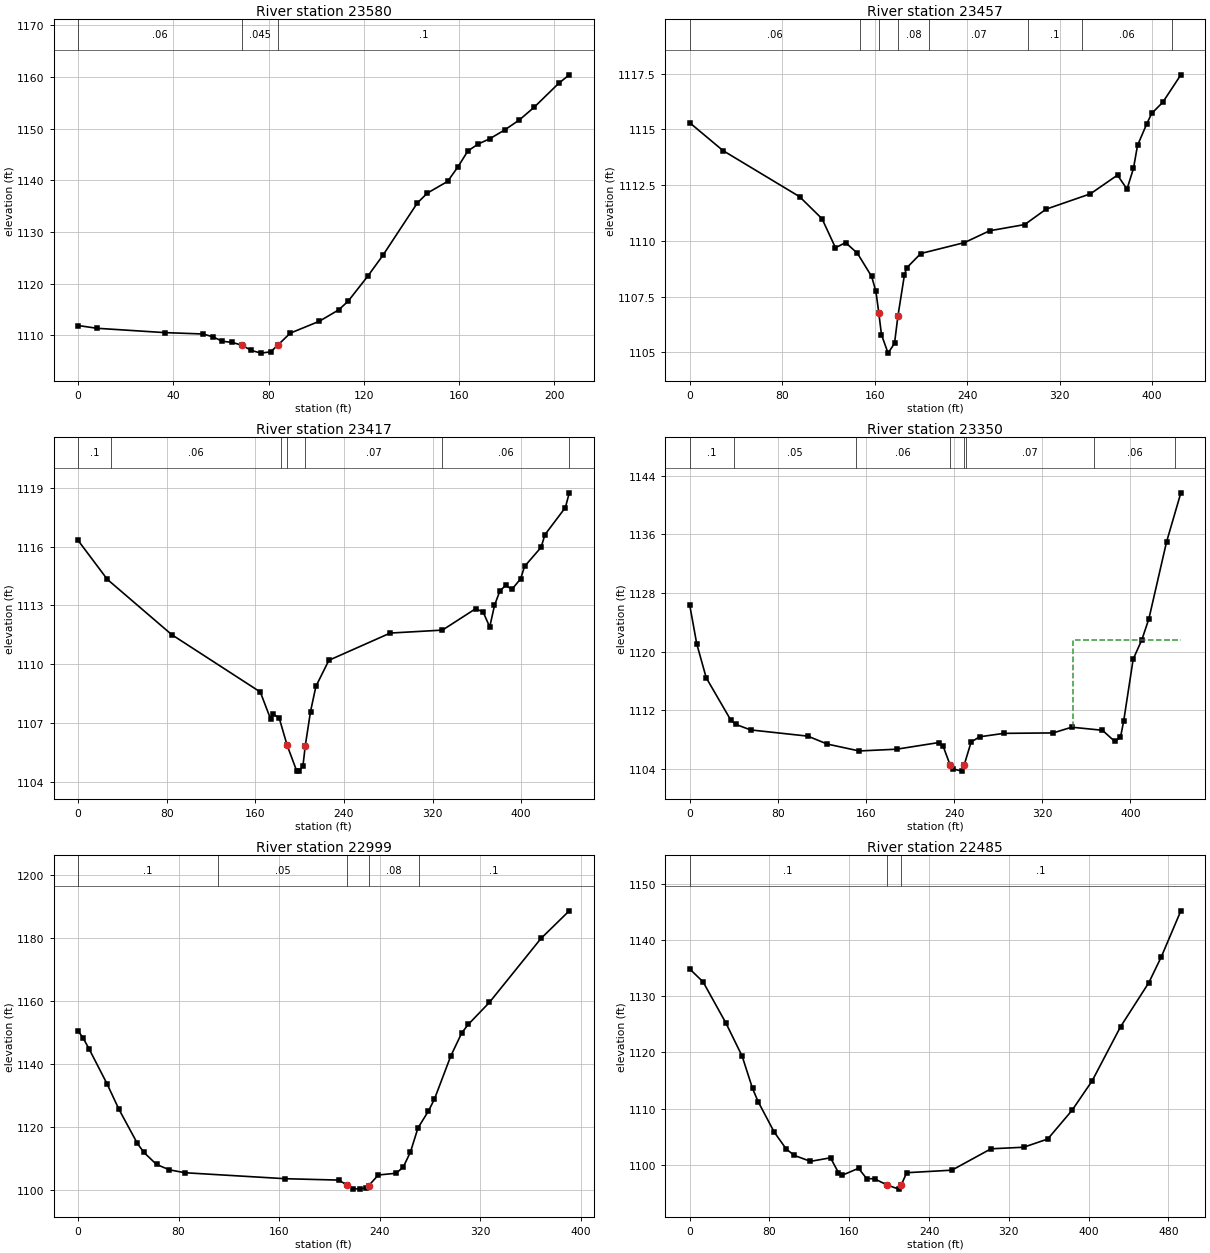
Type RM Length L Ch R = 1 ,23580   ,118.1,123.3,127.6
XS GIS Cut Line= 3
1644852.39169282432341.8967615011644978.47120613432364.067356535
1645052.26829339432337.867057644
#Sta/Elev= 30
       0 1111.93     7.8  1111.4    36.3 1110.56    52.5 1110.29    56.6 1109.74
    60.6 1108.88    64.7 1108.67    68.8 1108.12    72.8  1107.1    76.9 1106.59
    80.9 1106.85    83.81108.097    89.1 1110.45   101.3 1112.75   109.4 1114.94
   113.4 1116.62   121.6 1121.43     128 1125.49   142.5 1135.63   146.7 1137.54
   155.2  1139.8   159.5 1142.58   163.7 1145.68     168 1147.02   172.8 1148.02
   179.1 1149.73   185.3 1151.67   191.6 1154.16   201.9 1158.78   206.3 1160.41
#Mann= 3 ,-1,0
       0     .06       0    68.8    .045       0    83.8      .1       0
Bank Sta=68.8,83.8
XS Rating Curve= 0 ,0
Exp/Cntr(USF)=0,0
Exp/Cntr=0.3,0.1

Type RM Length L Ch R = 1 ,23457   ,40.2,40.2,39.8
XS GIS Cut Line= 6
1644832.83508847432335.6212803481644913.34780752432446.497496446
 1645010.0323472432555.6320349071645028.78295108432574.279771367
1645084.43966896432629.1150468871645120.47640086432639.511315129
#Sta/Elev= 30
       0  1115.3    28.8 1114.05    95.1 1111.98   114.5 1110.99   126.1 1109.69
   134.9 1109.92   145.1 1109.44   157.4  1108.4   161.1 1107.73   163.61106.764
   165.9 1105.79   171.6 1104.96   177.2  1105.4   180.1 1106.61   185.8 1108.48
   187.8 1108.79   199.9 1109.43   237.7 1109.92   259.4 1110.45   289.8 1110.73
   308.3 1111.42   346.7 1112.11   370.1 1112.95   378.3 1112.32   383.9 1113.25
   387.4 1114.28   395.4 1115.25   399.7 1115.72   409.3 1116.22   424.9 1117.45
#Mann= 8 ,-1,0
       0     .06       0  147.02     .08       0   163.6    .045       0
   180.1     .08       0  207.02     .07       0  292.83      .1       0
  339.27     .06       0   417.4      .1       0
Bank Sta=163.6,180.1
XS Rating Curve= 0 ,0
Exp/Cntr(USF)=0,0
Exp/Cntr=0.3,0.1

Type RM Length L Ch R = 1 ,23417   ,70.2,66.7,62.4
XS GIS Cut Line= 5
1644802.87572821432355.463327596 1644900.7836973432485.795057845
1645014.14042966432606.8956990571645075.99957204432652.023881385
1645111.40780198432665.626528686
#Sta/Elev= 30
       0 1116.32    26.4 1114.33    84.5 1111.51   164.5 1108.58   173.7 1107.21
   175.8 1107.45   181.5 1107.26   188.7 1105.86   197.2 1104.57   199.6 1104.54
     203 1104.82   205.1 1105.84   209.8 1107.58   214.7 1108.87   226.4  1110.2
   281.8 1111.59   328.9 1111.74   358.8 1112.83   365.6 1112.67   371.6  1111.9
   375.9    1113   380.8 1113.75     386 1114.02   391.6 1113.82   399.5 1114.36
     403 1114.99     418 1115.97   421.4 1116.61   439.9    1118   443.4 1118.75
#Mann= 7 ,-1,0
       0      .1       0      30     .06       0  183.01     .07       0
   188.7    .045       0   205.1     .07       0  328.89     .06       0
  443.39      .1       0
Bank Sta=188.7,205.1
XS Rating Curve= 0 ,0
Exp/Cntr(USF)=0,0
Exp/Cntr=0.3,0.1

Type RM Length L Ch R = 1 ,23350   ,347.4,350.9,352.3
XS GIS Cut Line= 5
1644682.36299045 432486.209426671644755.36509676432521.557814989
1644987.43495051432602.2443535441645045.83663556432662.182925042
1645048.14196523432697.531313361
#Sta/Elev= 30
       0  1126.4     6.4 1121.09      15 1116.46    37.5 1110.64    41.9  1110.1
    55.3 1109.35   107.3  1108.5   124.9 1107.42   153.9 1106.48   187.9 1106.72
   225.9 1107.62   230.1 1107.13   236.3 1104.61   238.6 1104.05   247.1 1103.73
   249.21104.574   255.5  1107.7   263.2 1108.41   285.2 1108.88     330 1108.94
   346.8 1109.72   374.7  1109.3   385.9 1107.78   391.1 1108.35     394 1110.56
   402.6 1118.99   410.5 1121.65   416.9 1124.52   432.9 1134.98   445.9 1141.68
#Mann= 8 ,-1,0
       0      .1       0      40     .05       0  151.11     .06       0
   236.3    .045       0   249.2     .06       0  251.11     .07       0
  366.81     .06       0  440.49      .1       0
#XS Ineff= 2 , 0
                          348.31          1121.6
Permanent Ineff=
       F       F
Bank Sta=236.3,249.2
XS Rating Curve= 0 ,0
Exp/Cntr(USF)=0,0
Exp/Cntr=0.3,0.1

Type RM Length L Ch R = 1 ,22999   ,517.2,514.6,509.6
XS GIS Cut Line= 3
1644544.96176775432725.2444327221644579.50323797432748.067196485
1644855.62333533  432962.3058997
#Sta/Elev= 30
       0 1150.37     3.8 1148.26     8.6 1144.78      23  1133.6    32.5 1125.48
    47.2 1114.63    52.3 1111.81    62.4 1107.97    72.6 1106.26    84.9 1105.33
   164.8 1103.43   207.5 1102.99   214.3 1101.32   218.9 1100.29   224.4 1100.12
   229.5  1100.6   231.4 1101.27   238.9 1104.61   253.1 1105.16   258.8 1107.13
   264.5 1111.91   270.5 1119.56   278.8 1124.91   283.6 1128.71   296.6 1142.42
   305.4 1149.79   310.5 1152.44   327.3 1159.42   368.4 1179.76   390.9 1188.54
#Mann= 5 ,-1,0
       0      .1       0   111.4     .05       0   214.3    .045       0
   231.4     .08       0   271.4      .1       0
Bank Sta=214.3,231.4
XS Rating Curve= 0 ,0
Exp/Cntr(USF)=0,0
Exp/Cntr=0.3,0.1

Type RM Length L Ch R = 1 ,22485   ,204.1,207.8,208.5
XS GIS Cut Line= 4
1644252.05505028433235.5385159341644334.59154474 433224.15417187
1644562.27842603433248.8202506751644739.68445436433217.513304499
#Sta/Elev= 30
       0 1134.85    13.4 1132.56    36.4 1125.21    52.6 1119.34      63 1113.61
    68.7 1111.23    84.8 1105.83    96.9 1102.81     105 1101.69   121.1 1100.64
   141.2 1101.27   149.2 1098.62   153.2 1098.19   169.3  1099.4   177.4 1097.58
   185.4 1097.53   197.5 1096.47   209.6  1095.7   212.1 1096.44   217.6 1098.62
   262.9 1099.07   302.1 1102.87   334.9 1103.15     359 1104.61   383.3 1109.69
   403.6 1114.97     432 1124.57   460.4 1132.42     473 1137.05   492.5 1145.19
#Mann= 3 ,-1,0
       0      .1       0   197.5    .045       0   212.1      .1       0
Bank Sta=197.5,212.1
XS Rating Curve= 0 ,0
Exp/Cntr(USF)=0,0
Exp/Cntr=0.3,0.1

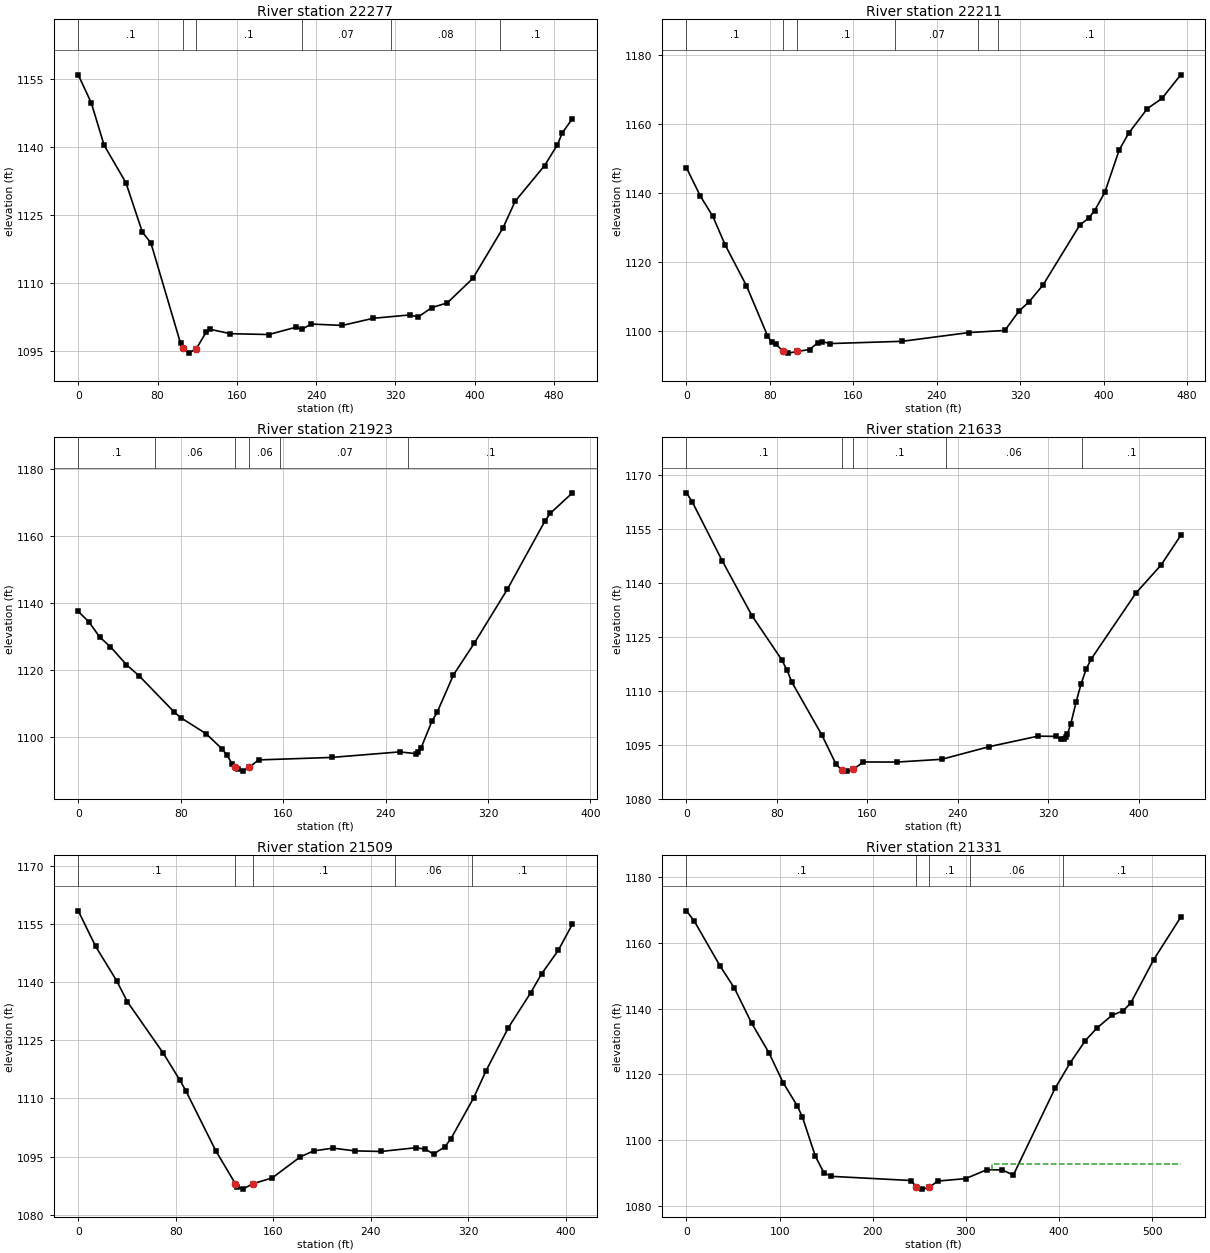
Type RM Length L Ch R = 1 ,22277   ,67.4,65.7,64.3
XS GIS Cut Line= 5
1644231.77084234433350.7427663481644358.70357372433399.748441123
1644375.57437979433381.2708916181644418.95645254433371.630431006
1644694.51295168433472.051895708
#Sta/Elev= 30
       0 1155.97    13.2 1149.75    26.1 1140.45    48.1 1132.18    64.7 1121.29
    73.3 1118.91   103.3 1096.73     1061095.649   111.8  1094.6   119.1 1095.56
     129 1099.19   133.3 1099.84   153.5 1098.89   192.3  1098.7   219.5  1100.3
   225.9 1099.88   235.2 1101.01   266.6 1100.71   297.6 1102.28   334.5 1103.02
     343 1102.57   356.9 1104.64   372.5 1105.69   398.3 1111.09   428.7 1122.21
   440.9 1128.07   470.7 1135.97   483.5  1140.5   488.5 1143.16   498.8 1146.32
#Mann= 6 ,-1,0
       0      .1       0     106    .045       0   119.1      .1       0
  225.53     .07       0  315.53     .08       0  425.53      .1       0
Bank Sta=106,119.1
XS Rating Curve= 0 ,0
Exp/Cntr(USF)=0,0
Exp/Cntr=0.3,0.1

Type RM Length L Ch R = 1 ,22211   ,287.2,288.4,288.1
XS GIS Cut Line= 3
1644227.07652518 433443.045111081644513.58251746 433479.09553395
1644675.80942037433568.272895786
#Sta/Elev= 30
       0 1147.32    13.1 1139.24    25.2 1133.28    37.3  1124.8    57.5 1113.09
    77.6 1098.61    81.7 1096.59    85.7 1096.12    92.81093.986    97.8  1093.5
   106.1 1093.98     118 1094.55     126 1096.51   130.1 1096.82   137.8 1096.28
   206.7 1096.93   270.8 1099.47   305.3 1100.09     319 1105.79   328.2 1108.31
   341.8 1113.25   377.1 1130.69   385.9 1132.79   391.4 1134.92   401.2 1140.27
   414.9  1152.5     424 1157.39   441.9 1164.53     456  1167.5   473.9 1174.35
#Mann= 6 ,-1,0
       0      .1       0    92.8    .045       0   106.1      .1       0
     200     .07       0     280     .08       0  298.77      .1       0
Bank Sta=92.8,106.1
XS Rating Curve= 0 ,0
Exp/Cntr(USF)=0,0
Exp/Cntr=0.3,0.1

Type RM Length L Ch R = 1 ,21923   ,287.3,289.4,289.8
XS GIS Cut Line= 4
1644175.98231888433705.5695427291644260.31079343433730.165347805
1644427.79651372433765.3022122011644548.43308148433805.123991849
#Sta/Elev= 30
       0 1137.41     8.5 1134.19    16.8 1129.72    25.1 1126.86    37.6  1121.5
    47.7  1118.1    75.1 1107.28    79.9  1105.7    99.9 1100.85   112.2 1096.37
   116.3 1094.38   120.3 1091.82   122.81090.885   124.4 1090.29   128.5 1089.69
   133.6 1090.85   140.8 1093.04   197.8 1093.78   251.1 1095.44   263.5 1094.91
     265 1095.39   267.7 1096.58   276.2 1104.55   280.4 1107.34     293 1118.41
   309.3  1127.9   335.1 1143.99   364.6 1164.48   368.8 1166.76     386 1172.84
#Mann= 6 ,-1,0
       0      .1       0      60     .06       0   122.8    .045       0
   133.6     .06       0  157.84     .07       0  257.84      .1       0
Bank Sta=122.8,133.6
XS Rating Curve= 0 ,0
Exp/Cntr(USF)=0,0
Exp/Cntr=0.3,0.1

Type RM Length L Ch R = 1 ,21633   ,124.4,124.3,124
XS GIS Cut Line= 2
1644023.56201748433921.1329766821644419.95958008434105.894552468
#Sta/Elev= 30
       0 1165.08       5 1162.62    31.5 1146.24      58 1130.88    84.3 1118.62
    88.9 1115.78    93.3 1112.37   119.8  1097.7   132.4 1089.52   137.4 1087.96
   141.8 1087.65   147.5 1088.11   156.5  1090.2     186 1090.17   225.8 1090.94
   267.9 1094.46     311 1097.38   327.2 1097.32   331.6 1096.45   334.1 1096.58
     336 1097.04   337.1 1097.91   340.1 1100.86   344.8 1106.95   349.2 1111.98
   353.7 1116.05   358.1 1118.85   397.8 1137.24   419.9 1144.98   437.3 1153.21
#Mann= 5 ,-1,0
       0      .1       0   137.4    .045       0   147.5      .1       0
     230     .06       0     350      .1       0
Bank Sta=137.4,147.5
XS Rating Curve= 0 ,0
Exp/Cntr(USF)=0,0
Exp/Cntr=0.3,0.1

Type RM Length L Ch R = 1 ,21509   ,178.8,177.4,175.8
XS GIS Cut Line= 3
1643982.80532238434047.2921346891644264.77865915 434159.44900584
1644354.27225277434208.464931672
#Sta/Elev= 30
       0 1158.37    14.3 1149.18    31.5 1140.36    40.2 1134.98    69.7  1121.7
    83.2 1114.81    88.2 1112.03   112.8 1096.54   128.91088.034   130.6 1087.29
   134.9 1086.63   143.5 1088.05     159 1089.49   182.2 1094.95   193.1 1096.48
     209  1097.2   226.8 1096.49   248.4 1096.34   276.9  1097.3   284.8 1096.94
   291.5 1095.66   300.7 1097.53   305.7 1099.58   324.4 1110.15   334.6 1117.15
   352.9 1128.24   371.1 1137.19   380.2 1142.14   393.9  1148.2   405.5 1154.96
#Mann= 5 ,-1,0
       0      .1       0   128.9    .045       0   143.5      .1       0
     260     .06       0  323.46      .1       0
Bank Sta=128.9,143.5
XS Rating Curve= 0 ,0
Exp/Cntr(USF)=0,0
Exp/Cntr=0.3,0.1

Type RM Length L Ch R = 1 ,21331   ,334.2,337.1,332.2
XS GIS Cut Line= 3
1643867.35450341434154.6044224481643963.09459268434248.664861029
1644352.77355252434320.889840655
#Sta/Elev= 30
       0  1169.7     8.5 1166.51    35.8 1153.05    51.5 1146.18    69.8 1135.61
    88.4  1126.6   103.7 1117.47   118.8 1110.45   124.4 1107.04   138.4 1095.04
   147.5 1090.06   155.6 1088.97     241 1087.71  246.79 1085.77   253.2 1085.09
   260.61085.612   269.5 1087.53   299.7 1088.29   322.4 1090.99   338.7 1090.93
   350.9 1089.39   395.6 1115.71   411.9  1123.5   428.2 1130.27   440.4 1134.01
   456.6 1137.92   468.8 1139.31     477 1141.73   501.4  1154.8   530.5 1167.77
#Mann= 5 ,-1,0
       0      .1       0  246.79    .045       0   260.6      .1       0
  304.21     .06       0  404.21      .1       0
#XS Ineff= 2 , 0
                          327.76         1092.68
Permanent Ineff=
       F       F
Bank Sta=246.79,260.6
XS Rating Curve= 0 ,0
Exp/Cntr(USF)=0,0
Exp/Cntr=0.3,0.1

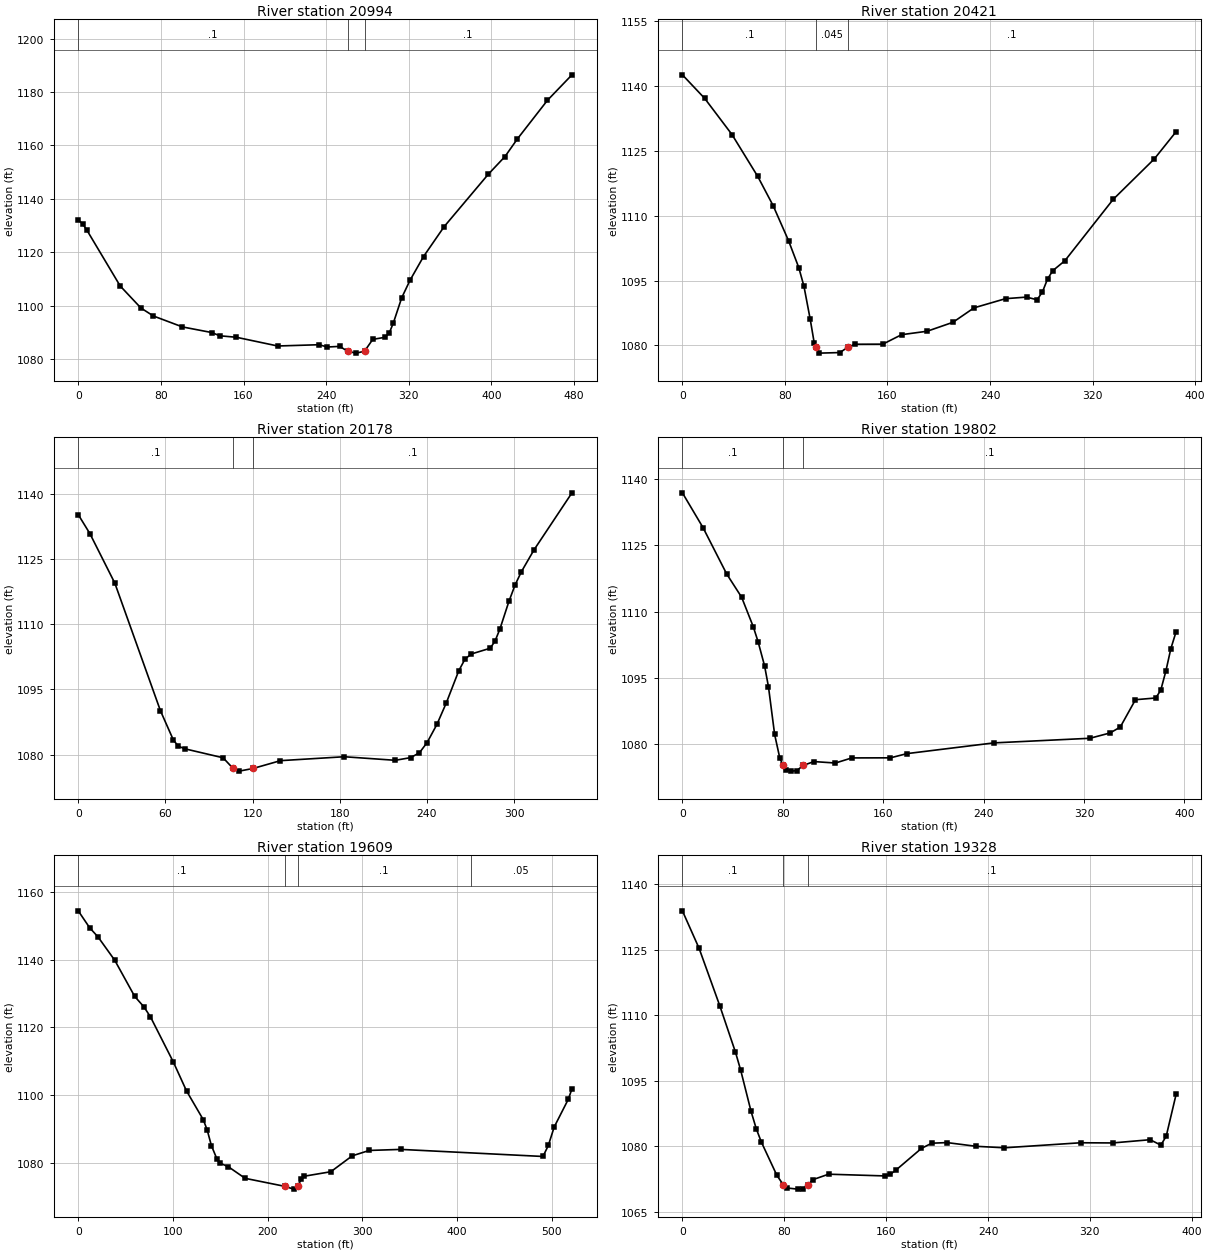
Type RM Length L Ch R = 1 ,20994   ,566,573.8,570.1
XS GIS Cut Line= 4
1643827.75275023434563.4444146131643946.64291783434550.591423522
1644160.32389472434547.3781757491644304.92004449434547.378175749
#Sta/Elev= 30
       0 1132.05     4.4 1130.55     8.4 1128.23    40.6 1107.35    60.7 1099.08
    72.8 1096.09   100.9    1092   129.1 1089.91   137.1 1088.68   153.1 1088.13
   193.1 1084.86   233.1 1085.34   241.1 1084.48   253.1 1084.72   261.1 1082.81
   269.1 1082.19   277.1  1082.9   285.1 1087.34   297.1 1088.13   301.1 1089.76
   305.1 1093.59   313.1 1102.91   321.1 1109.44   334.2 1118.35   354.2 1129.57
   397.1 1149.27   413.1 1155.83   425.1 1162.43   454.2 1176.89   477.9 1186.42
#Mann= 3 ,-1,0
       0      .1       0   261.1    .045       0   277.1      .1       0
Bank Sta=261.1,277.1
XS Rating Curve= 0 ,0
Exp/Cntr(USF)=0,0
Exp/Cntr=0.3,0.1

Type RM Length L Ch R = 1 ,20421   ,238,242.8,244.2
XS GIS Cut Line= 5
1643893.42137827  435022.34213971643960.01979104435025.757442919
1644103.46252625435034.2957009671644181.16067449435052.226042869
1644262.27412595435101.747939548
#Sta/Elev= 30
       0 1142.63    17.4 1137.17    38.7  1128.8    58.8  1119.1    70.8 1112.34
    82.8 1104.25    90.8    1098    94.8 1093.73    99.7 1086.08   102.8 1080.65
   104.61079.574   106.9  1078.2   122.9 1078.33   129.41079.649   134.9 1080.26
   156.4 1080.28     171 1082.47     191 1083.27   211.1 1085.34   227.5 1088.68
   252.1 1090.81   268.5 1091.17   276.7 1090.55   280.8 1092.31   284.9 1095.37
     289  1097.3   298.4 1099.59   336.1  1113.8   368.2 1123.17   385.2 1129.47
#Mann= 3 ,-1,0
       0      .1       0   104.6    .045       0   129.4      .1       0
Bank Sta=104.6,129.4
XS Rating Curve= 0 ,0
Exp/Cntr(USF)=0,0
Exp/Cntr=0.3,0.1

Type RM Length L Ch R = 1 ,20178   ,373.5,375.7,371.9
XS GIS Cut Line= 4
1643863.74548015435185.7122901091643912.23435302435221.551891793
1644087.21593771435300.6098366831644168.38209446435333.287120571
#Sta/Elev= 30
       0 1135.21       8 1130.86    25.2 1119.44    56.6 1090.08    65.5 1083.35
    68.9 1081.95    73.3 1081.35    99.7 1079.28   106.61076.822   110.8 1076.21
   120.41076.827   139.2 1078.62   183.1 1079.52   218.2  1078.7   228.7 1079.31
   234.8 1080.42   240.1 1082.78   246.9 1086.98   253.3 1091.89   261.9  1099.3
   266.2 1101.98   270.5 1103.15   283.5 1104.47   286.8 1106.08   290.2 1108.88
   296.4 1115.24   300.7 1119.07     305 1122.08   313.6 1127.06   339.8 1140.22
#Mann= 3 ,-1,0
       0      .1       0   106.6    .045       0   120.4      .1       0
Bank Sta=106.6,120.4
XS Rating Curve= 0 ,0
Exp/Cntr(USF)=0,0
Exp/Cntr=0.3,0.1

Type RM Length L Ch R = 1 ,19802   ,191.2,193.1,190.9
XS GIS Cut Line= 3
1643697.19674292435476.6455273051643910.12614115435573.623273036
1644068.24203093435593.651285742
#Sta/Elev= 30
       0 1136.95    16.4 1129.07    35.3 1118.52    47.2 1113.24    56.5 1106.52
    60.3 1103.15    65.5 1097.64    68.6 1092.88    73.5 1082.07    77.6 1076.73
    80.11075.125    82.3 1074.09    86.7 1073.75    91.1 1073.85    96.2 1075.04
   104.8 1075.92   121.9 1075.59     135 1076.75   165.8 1076.77     179 1077.73
   248.1 1080.16   324.7 1081.21   340.8 1082.42   348.9 1083.76     361 1089.97
   377.1 1090.36   381.1 1092.08   385.2 1096.44   389.2 1101.57   393.4 1105.43
#Mann= 3 ,-1,0
       0      .1       0    80.1    .045       0    96.2      .1       0
Bank Sta=80.1,96.2
XS Rating Curve= 0 ,0
Exp/Cntr(USF)=0,0
Exp/Cntr=0.3,0.1

Type RM Length L Ch R = 1 ,19609   ,282.4,280.9,278.8
XS GIS Cut Line= 3
1643561.16444112435692.8711989691643664.75420992 435644.38237102
1644026.21638191435831.725569915
#Sta/Elev= 30
       0  1154.4    12.1 1149.39    20.9 1146.69    38.6 1139.78    59.6 1129.13
    69.5 1125.98    76.3 1123.06   100.4 1109.76   114.4 1101.17   132.1 1092.67
   136.2 1089.64   140.7 1084.99   146.7 1080.94   149.7 1079.86   158.7 1078.75
   176.3 1075.35   217.9    1073   227.7 1072.16  231.85 1073.05   235.7 1075.13
   238.6 1075.97   266.8  1077.3   289.4    1082   307.4 1083.59   340.7  1083.9
   490.9 1081.81   496.6 1085.11   502.7  1090.5   517.6  1098.7   521.5  1101.8
#Mann= 4 ,-1,0
       0      .1       0   217.9    .045       0  231.85      .1       0
  414.38     .05       0
Bank Sta=217.9,231.85
XS Rating Curve= 0 ,0
Exp/Cntr(USF)=0,0
Exp/Cntr=0.3,0.1

Type RM Length L Ch R = 1 ,19328   ,277.2,278.7,278.5
XS GIS Cut Line= 4
1643575.29545075435896.6933893161643619.56789989435906.180342703
1643785.06253119435933.5870969311643951.61126843435986.292393525
#Sta/Elev= 30
       0 1133.96    13.1 1125.38    29.5  1112.1    41.7 1101.56    45.8 1097.43
    53.9 1088.04      58 1084.05      62 1080.99    74.2 1073.36    79.31071.182
    82.3 1070.47    90.4 1070.21    94.5 1070.34    98.5 1071.17   102.6 1072.39
   114.8 1073.63   159.4 1073.23   163.4 1073.65   167.5 1074.52   187.7 1079.54
   195.8 1080.73   207.8 1080.87   230.6 1080.02   252.9 1079.68   312.7 1080.83
   337.9 1080.79   367.3 1081.53   375.7 1080.29   379.9 1082.32   387.7 1091.94
#Mann= 3 ,-1,0
       0      .1       0    79.3    .045       0    98.5      .1       0
Bank Sta=79.3,98.5
XS Rating Curve= 0 ,0
Exp/Cntr(USF)=0,0
Exp/Cntr=0.3,0.1

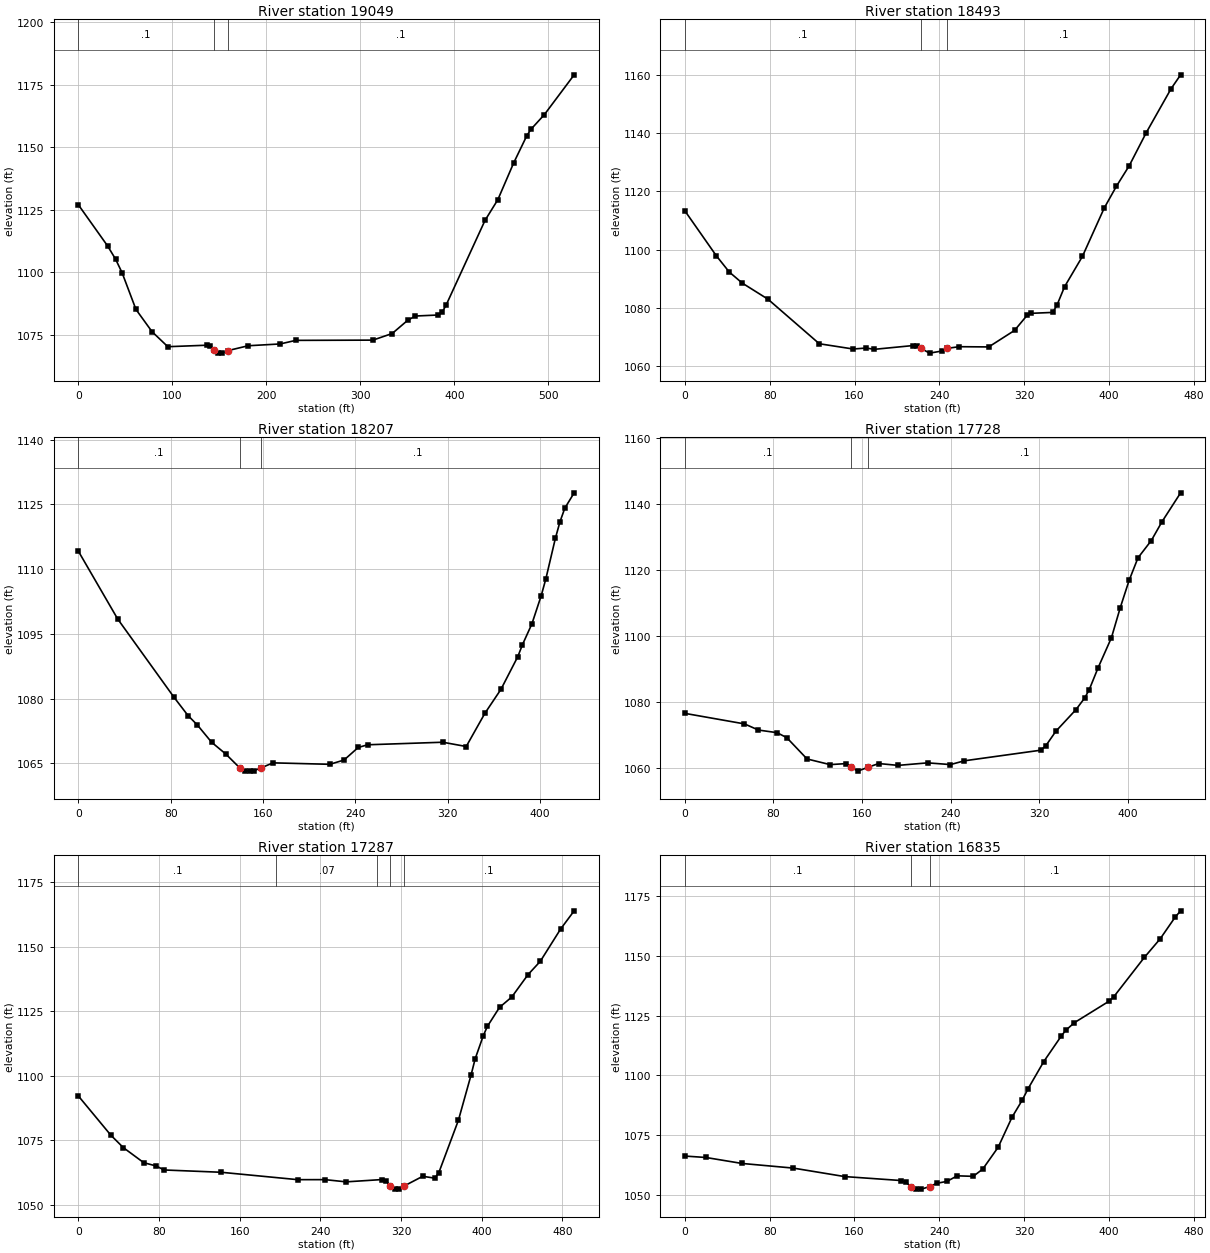
Type RM Length L Ch R = 1 ,19049   ,552.1,556,550.5
XS GIS Cut Line= 5
1643494.17491022  436111.13141731643548.98841867436150.133336779
1643734.51106268436196.5139977811643885.24821094436229.191281669
1643990.65880413436274.517836739
#Sta/Elev= 30
       0 1126.98    31.1 1110.54    39.7 1105.18    46.6 1099.76    61.3 1085.14
    78.4 1076.25    95.2 1070.24   136.5 1070.83   140.6  1070.7   144.4 1068.76
   148.8 1067.68     153 1067.67   159.41068.701   180.7 1070.62   214.8 1071.34
   231.3 1072.77   313.4 1072.87   333.9 1075.51   350.2 1080.73   358.4  1082.5
   382.9 1082.91     387 1084.02   391.1 1086.73   432.7 1120.75   446.3 1129.01
   463.1 1143.66   476.8 1154.33   481.4 1157.09   495.9 1163.06   527.5 1178.92
#Mann= 3 ,-1,0
       0      .1       0   144.4    .045       0   159.4      .1       0
Bank Sta=144.4,159.4
XS Rating Curve= 0 ,0
Exp/Cntr(USF)=0,0
Exp/Cntr=0.3,0.1

Type RM Length L Ch R = 1 ,18493   ,280.8,286.5,287.8
XS GIS Cut Line= 4
1643398.79860398  436598.46648891643502.90783182436615.818026873
1643758.84301692436617.2639883711643864.39820626436625.939757357
#Sta/Elev= 30
       0 1113.37    29.7  1097.9    41.9 1092.32    54.1 1088.52    78.4 1082.97
   126.8 1067.66   158.8 1065.85   170.8 1066.19   178.8 1065.75   214.8 1067.03
   218.7 1066.94   222.7 1066.07   230.7 1064.44   242.8 1065.19   246.8 1066.06
   258.8 1066.65   286.5 1066.57   310.8 1072.23   322.8 1077.48   326.8 1078.12
   346.8 1078.43   350.8 1080.89     358 1087.26   374.8 1097.66   395.4 1114.31
   406.9  1121.8   418.9  1128.8     435  1140.2   458.4  1155.3   467.4 1160.07
#Mann= 3 ,-1,0
       0      .1       0   222.7    .045       0   246.8      .1       0
Bank Sta=222.7,246.8
XS Rating Curve= 0 ,0
Exp/Cntr(USF)=0,0
Exp/Cntr=0.3,0.1

Type RM Length L Ch R = 1 ,18207   ,477.7,478.5,463
XS GIS Cut Line= 4
1643370.54483764436832.668551367 1643471.7390071436850.588352209
1643628.80079094436885.3738479611643792.18721038436913.834708121
#Sta/Elev= 30
       0 1114.17    34.1 1098.43    82.8 1080.31      95 1076.05   103.2 1073.83
   115.4 1069.87   127.7 1067.13     140 1063.87   144.1 1063.27   148.3 1063.16
   152.3 1063.26     1581063.885   168.7 1065.08   217.9 1064.74   230.2 1065.74
   242.4 1068.64   250.6 1069.27   315.7 1069.86     336 1068.87   352.2 1076.58
   366.1 1082.13   380.7 1089.72   384.7 1092.47   392.9 1097.31     401 1103.88
     405 1107.77   413.2 1117.11   417.2 1120.97   421.4 1124.13   429.5 1127.69
#Mann= 3 ,-1,0
       0      .1       0     140    .045       0     158      .1       0
Bank Sta=140,158
XS Rating Curve= 0 ,0
Exp/Cntr(USF)=0,0
Exp/Cntr=0.3,0.1

Type RM Length L Ch R = 1 ,17728   ,436.2,441.8,440.2
XS GIS Cut Line= 4
1643360.75233262437278.5435926341643444.23752243437251.980123151
1643673.82179439437122.9575570911643770.58871893437127.701033784
#Sta/Elev= 30
       0 1076.65    53.9 1073.46    66.5  1071.6    83.3 1070.81    92.1  1069.3
   110.4 1062.86   131.2 1061.15   145.9 1061.46   150.21060.333   156.3 1059.18
   165.61060.379   175.2 1061.47   192.6 1060.92   219.3 1061.68   239.9 1061.16
   252.6 1062.31   321.5 1065.51   326.1 1066.88   335.2 1071.27   353.3 1077.78
   361.3 1081.37   365.3 1083.85   373.3 1090.46   385.3 1099.51   393.3 1108.63
   401.3 1116.88   409.3 1123.68   421.3 1128.89     431 1134.61   447.8 1143.33
#Mann= 3 ,-1,0
       0      .1       0   150.2    .045       0   165.6      .1       0
Bank Sta=150.2,165.6
XS Rating Curve= 0 ,0
Exp/Cntr(USF)=0,0
Exp/Cntr=0.3,0.1

Type RM Length L Ch R = 1 ,17287   ,453.9,451.3,442.9
XS GIS Cut Line= 4
1643348.00719419437553.1840730641643472.95773324437533.888403119
1643747.06090654437528.7276305431643837.39745925437516.349688747
#Sta/Elev= 30
       0 1092.11    32.2 1076.91    44.6 1072.08    64.9 1066.22      77 1064.97
    85.1  1063.4   141.6 1062.51   217.6 1059.64   244.7 1059.65   265.6 1058.79
   301.6 1059.69   305.6 1059.08   309.31057.233   313.6 1055.97   317.6 1056.04
   323.21057.195   341.6 1060.95   353.6 1060.22   357.6  1062.4     377 1082.69
   389.6 1100.32   393.6 1106.49   401.6 1115.41   405.7 1119.08   417.8 1126.47
   429.9 1130.47   446.1 1139.19   458.2 1144.31   478.4 1156.86   491.8  1163.9
#Mann= 5 ,-1,0
       0      .1       0  196.43     .07       0  296.43      .1       0
   309.3    .045       0   323.2      .1       0
Bank Sta=309.3,323.2
XS Rating Curve= 0 ,0
Exp/Cntr(USF)=0,0
Exp/Cntr=0.3,0.1

Type RM Length L Ch R = 1 ,16835   ,168.9,173.2,177
XS GIS Cut Line= 4
1643540.06091227438072.5370934041643618.14283315438002.263364613
 1643809.4435393437873.4281951631643936.97734341437839.592696115
#Sta/Elev= 30
       0 1066.25    19.9 1065.65    53.8 1063.16   102.3 1061.21   150.8 1057.66
   203.9 1056.01   208.6 1055.19   213.5 1053.44   218.3 1052.47   223.2 1052.41
   230.91053.478   237.6 1054.84   247.3 1055.66   256.9 1057.98     272 1057.76
     281 1060.81   295.5 1069.92   308.6  1082.5   318.1 1089.55   323.8 1094.48
   338.5 1105.76   355.1  1116.5   359.1 1118.79   367.4 1122.06   400.2 1131.07
   404.7 1132.98   433.4 1149.37   448.4 1157.19   462.6 1166.31   467.6 1168.86
#Mann= 3 ,-1,0
       0      .1       0   213.5    .045       0   230.9      .1       0
Bank Sta=213.5,230.9
XS Rating Curve= 0 ,0
Exp/Cntr(USF)=0,0
Exp/Cntr=0.3,0.1

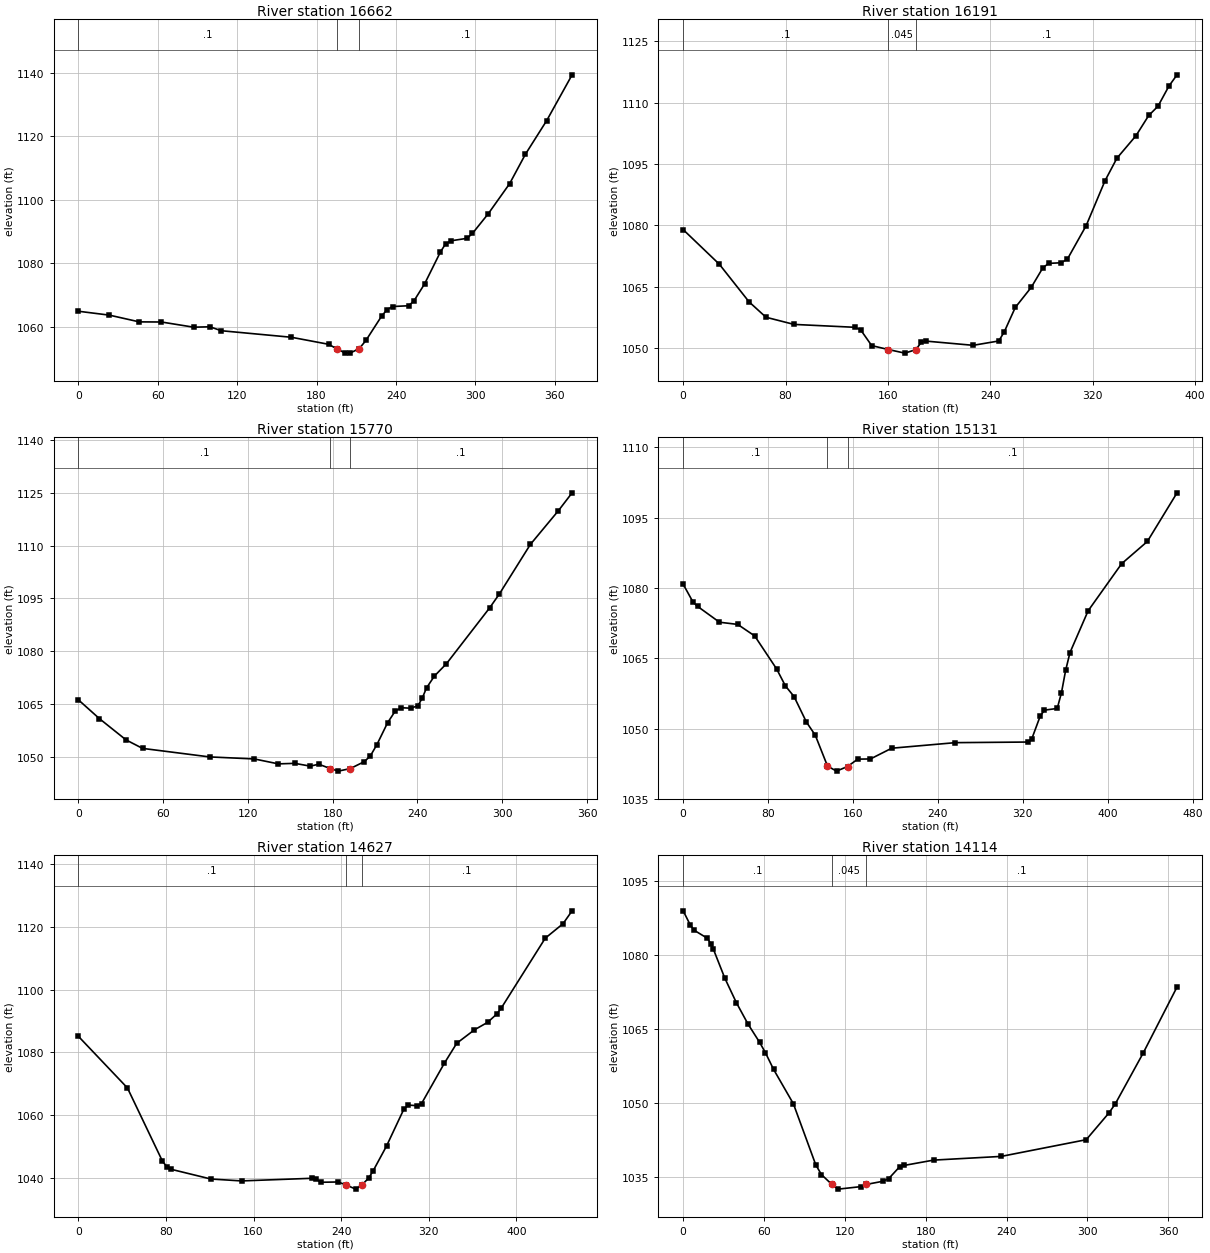
Type RM Length L Ch R = 1 ,16662   ,470.2,471.5,465.8
XS GIS Cut Line= 4
1643601.85385998438132.6653201041643717.97416944438093.389333083
1643879.34724655438075.4589911821643967.29130444438071.189862158
#Sta/Elev= 30
       0 1064.99    23.5 1063.76    46.1 1061.64    62.8  1061.6    87.1 1059.97
    99.5 1060.09     108 1058.86     161  1056.8   189.1 1054.59   195.2  1053.2
   201.2 1051.91   205.2 1051.81   212.2 1053.21   217.3 1055.81   229.4 1063.62
   233.4 1065.53   237.4 1066.47   249.5 1066.71   253.5  1068.2   261.6 1073.59
   273.6 1083.66   277.4 1086.15   281.7 1087.15   293.7 1087.92   297.7 1089.44
   309.7 1095.66   325.8  1105.1   337.8  1114.4   353.8 1124.94     373 1139.34
#Mann= 3 ,-1,0
       0      .1       0   195.2    .045       0   212.2      .1       0
Bank Sta=195.2,212.2
XS Rating Curve= 0 ,0
Exp/Cntr(USF)=0,0
Exp/Cntr=0.3,0.1

Type RM Length L Ch R = 1 ,16191   ,426.4,421,414.4
XS GIS Cut Line= 4
1643681.31492448438575.0511094681643772.41049884438533.407418333
1643942.88935942438464.4350548891644026.17674169 438405.87361423
#Sta/Elev= 30
       0 1078.94    28.2  1070.5    51.5 1061.28    64.7 1057.52    86.6 1055.77
   134.4 1055.06   138.7 1054.43   147.3 1050.59   160.3 1049.63   173.2 1048.75
   181.8  1049.6   186.1 1051.42   189.7 1051.69   226.6 1050.66   246.6 1051.72
   250.9 1053.95   259.5 1059.91     272 1064.84   281.1 1069.63   285.6 1070.69
   295.3 1070.84   300.2 1071.71   314.9 1079.92   329.6 1090.87   338.9 1096.39
   353.8 1101.89   363.8 1106.85     371  1109.1   379.6 1114.05   385.9 1116.78
#Mann= 3 ,-1,0
       0      .1       0   160.3    .045       0   181.8      .1       0
Bank Sta=160.3,181.8
XS Rating Curve= 0 ,0
Exp/Cntr(USF)=0,0
Exp/Cntr=0.3,0.1

Type RM Length L Ch R = 1 ,15770   ,627.7,638.8,640.3
XS GIS Cut Line= 4
1643956.67424526438832.4639191231643992.98233847438784.443537782
 1644128.8448808438639.2111649471644194.43369434438577.136037848
#Sta/Elev= 30
       0 1066.22      15 1060.83    33.8  1054.8    45.5 1052.38    92.9 1049.96
   124.6 1049.38   141.6 1047.98   153.2 1048.13   164.1 1047.34   170.2 1047.88
   178.4 1046.64     184 1045.92   192.5 1046.65   202.5 1048.64   206.7 1050.27
   211.2 1053.37   218.9 1059.69   224.4 1063.06   228.7 1063.93   235.4  1063.8
   240.4 1064.53   243.5 1066.78   246.4 1069.56     252 1072.94   260.5 1076.44
   291.1 1092.33   297.9 1096.23   319.9 1110.35   339.7 1119.92   349.4    1125
#Mann= 3 ,-1,0
       0      .1       0   178.4    .045       0   192.5      .1       0
Bank Sta=178.4,192.5
XS Rating Curve= 0 ,0
Exp/Cntr(USF)=0,0
Exp/Cntr=0.3,0.1

Type RM Length L Ch R = 1 ,15131   ,502.4,503.9,502
XS GIS Cut Line= 5
1644095.13890341439082.7451765871644190.13857381439056.717869627
1644337.19285813439058.019234975 1644453.0143741439060.621965671
1644555.82223659439076.238349847
#Sta/Elev= 30
       0 1080.81     9.3 1076.99    13.5 1076.09    34.2  1072.7    51.4 1072.23
    67.4 1069.77    88.1 1062.71    96.4 1059.08   104.5 1056.83   116.1  1051.4
   124.5 1048.57     136 1041.99   144.5 1040.91   154.91041.897   164.5 1043.47
   176.5 1043.51   196.5  1045.8   256.5 1046.99   325.2 1047.12   328.5 1047.79
   336.5 1052.68   340.5 1053.93   352.5 1054.29   356.5 1057.66   360.4  1062.4
   364.5 1066.21   381.6 1075.13   413.2 1085.19   437.4 1089.93   465.4 1100.32
#Mann= 3 ,-1,0
       0      .1       0     136    .045       0   154.9      .1       0
Bank Sta=136,154.9
XS Rating Curve= 0 ,0
Exp/Cntr(USF)=0,0
Exp/Cntr=0.3,0.1

Type RM Length L Ch R = 1 ,14627   ,508.2,513,507.1
XS GIS Cut Line= 3
1644135.34972405439485.7967291341644490.62246405439509.221305398
1644584.32076911 439494.90628657
#Sta/Elev= 30
       0 1085.15    44.9 1068.63    76.9 1045.23    80.9 1043.47    84.9 1042.65
     121 1039.56   149.1 1038.95   213.2 1039.79   217.2 1039.57   221.2 1038.52
   237.3 1038.61   244.11037.711   253.3 1036.33     259 1037.68   265.3 1039.94
   269.3 1042.24   281.4 1050.07   297.4 1061.98   301.4 1063.15   309.4 1062.96
   313.4 1063.65   334.2 1076.51   345.5 1082.88   361.6 1087.16   373.7 1089.56
   381.8 1092.13   385.9 1093.98   426.3 1116.42   442.5 1121.03   450.8 1125.15
#Mann= 3 ,-1,0
       0      .1       0   244.1    .045       0     259      .1       0
Bank Sta=244.1,259
XS Rating Curve= 0 ,0
Exp/Cntr(USF)=0,0
Exp/Cntr=0.3,0.1

Type RM Length L Ch R = 1 ,14114   ,195.3,197.8,200.5
XS GIS Cut Line= 5
1644071.40003502439854.5725518211644126.42436466439876.392544611
1644271.57475148439918.1351395131644377.96660627439952.532169676
1644416.83348901439974.167416785
#Sta/Elev= 30
       0 1088.92     5.3 1086.04     8.2 1084.98      18 1083.36    20.6  1082.2
    22.3 1081.24    30.9  1075.3    39.5 1070.33    48.1 1066.02    56.7 1062.33
      61 1060.24    67.1 1056.84    81.8 1049.88    98.4 1037.53   102.6 1035.57
   110.21033.603   115.1 1032.62   131.7 1033.12   135.9 1033.57     148  1034.2
   152.5 1034.74   160.8 1037.19   164.1 1037.42   185.8 1038.49     236 1039.24
   299.1 1042.62   315.9 1048.01   320.6 1049.83   341.3 1060.11   366.5 1073.51
#Mann= 3 ,-1,0
       0      .1       0   110.2    .045       0   135.9      .1       0
Bank Sta=110.2,135.9
XS Rating Curve= 0 ,0
Exp/Cntr(USF)=0,0
Exp/Cntr=0.3,0.1