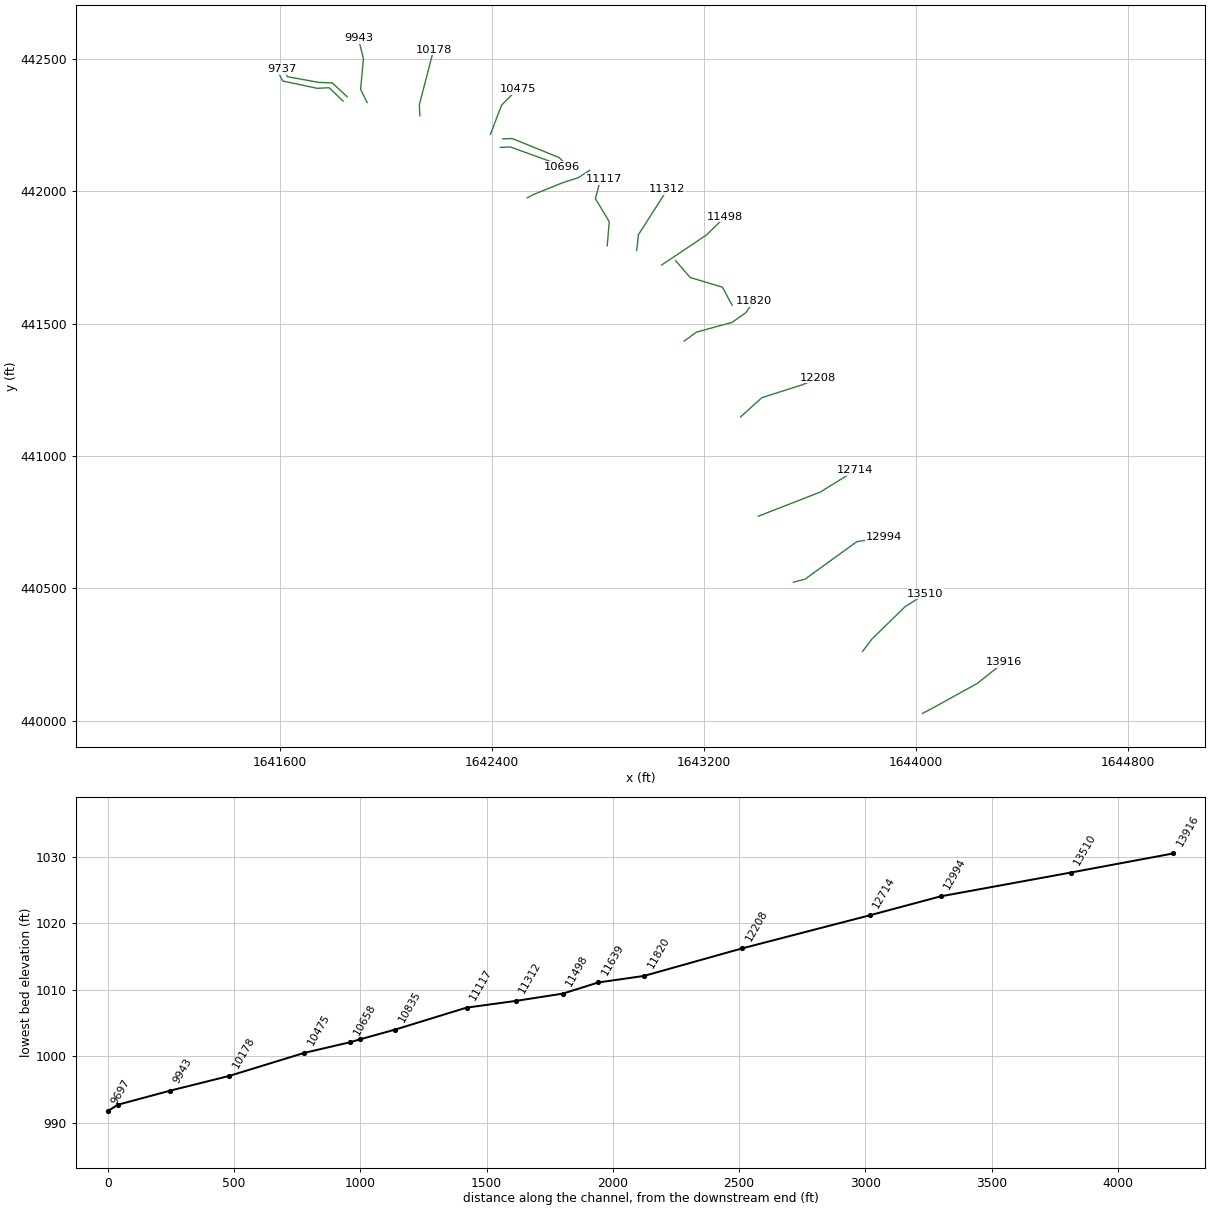
HEC-RAS study LYNNCMPRN.prj: LYNNCMPRN

--- LYNNCMPRN.g01 (geometry) --- (continued)

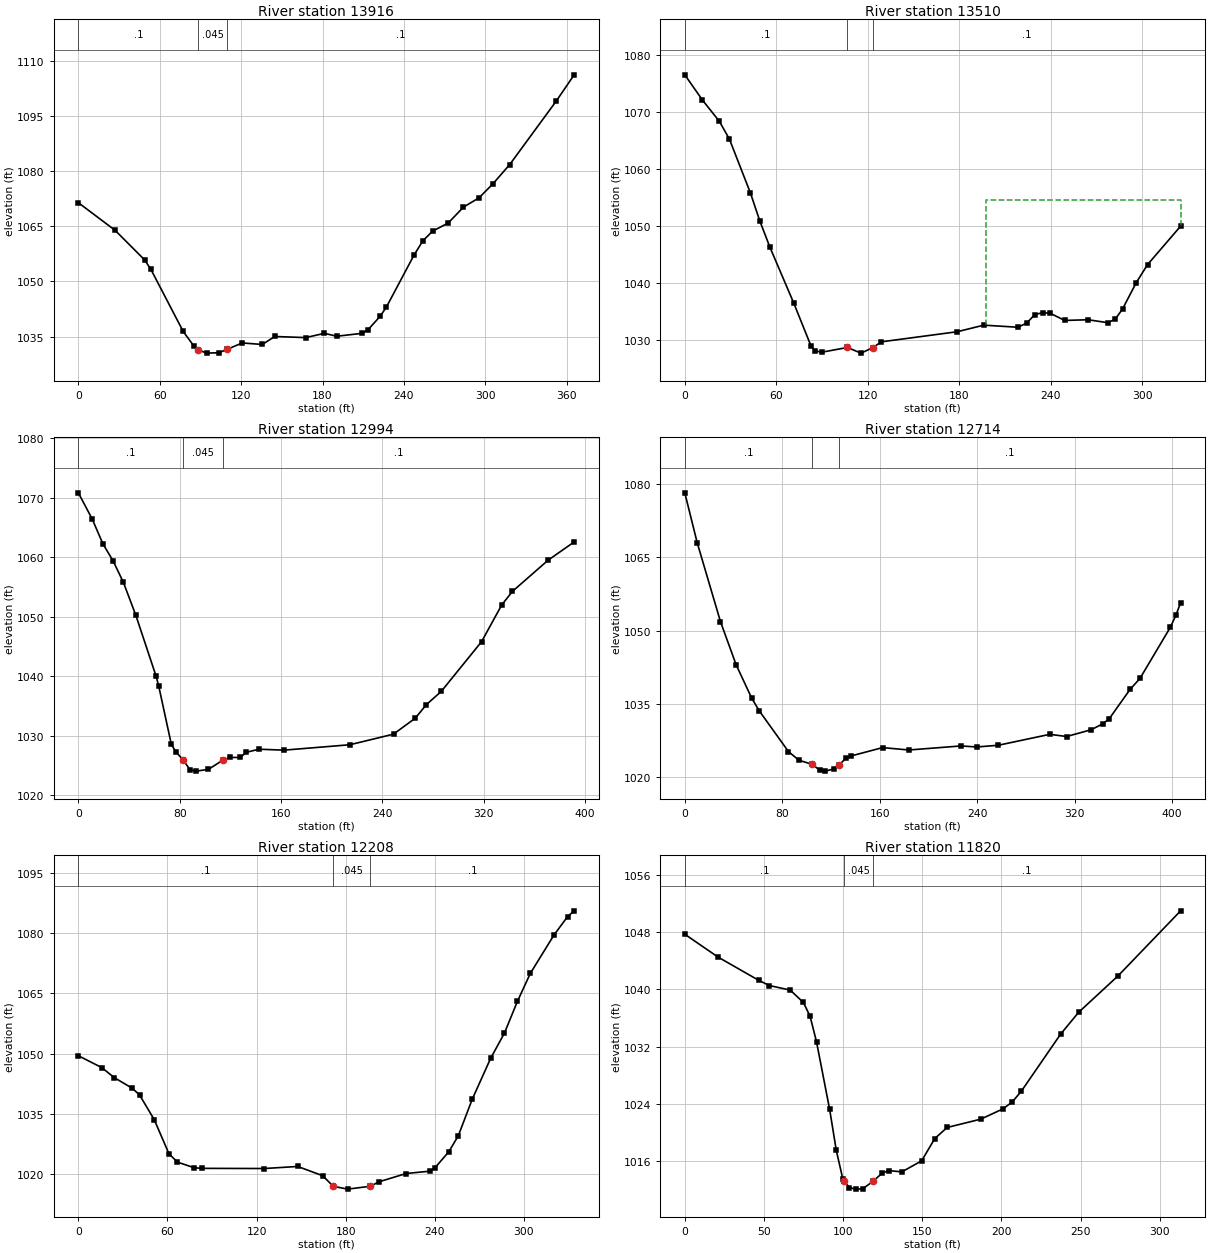
Type RM Length L Ch R = 1 ,13916   ,401.5,406.4,407.8
XS GIS Cut Line= 4
1644024.91387337440028.0614309861644060.05073776440046.280545858
 1644231.8309637440141.2802162611644333.33746084440221.964867836
#Sta/Elev= 30
       0 1071.41    27.1  1063.9    48.8 1055.89    53.4 1053.35    77.3 1036.42
    85.4 1032.34    88.4 1031.43    94.5 1030.53   103.6 1030.64   109.51031.525
   120.8  1033.3   135.6 1032.88   144.8 1035.05   167.6 1034.75   181.4 1035.91
   190.5 1035.12   208.8 1035.89   213.3 1036.78   222.5 1040.55   227.1 1043.05
   247.5  1057.2     254 1061.06   261.2 1063.69   272.6 1065.87   283.9  1070.2
   295.3 1072.71   305.4 1076.44     318 1081.77   352.3 1099.02   365.5 1106.15
#Mann= 3 ,-1,0
       0      .1       0    88.4    .045       0   109.5      .1       0
Bank Sta=88.4,109.5
XS Rating Curve= 0 ,0
Exp/Cntr(USF)=0,0
Exp/Cntr=0.3,0.1

Type RM Length L Ch R = 1 ,13510   ,509.7,515.4,493.6
XS GIS Cut Line= 4
1643798.44402575 440261.951551361643833.54575328440308.437622955
1643958.77353798440430.819321645  1644036.225914440480.161652756
#Sta/Elev= 30
       0  1076.6    11.6 1072.15    22.7 1068.41    29.3 1065.27      43 1055.85
    49.2  1050.9    55.9 1046.23    71.5 1036.43    82.8 1028.89    85.6 1028.04
    89.8 1027.81   106.6 1028.64   115.6 1027.65   123.21028.594     129 1029.64
   178.6 1031.41   196.1 1032.57   218.6  1032.2   224.4 1032.97   229.6 1034.44
   234.9 1034.77   239.7 1034.65   249.2  1033.4   264.5 1033.52   277.6    1033
   282.4 1033.66   287.1 1035.41   296.1 1040.05   303.5 1043.22   325.2 1049.98
#Mann= 3 ,-1,0
       0      .1       0   106.6    .045       0   123.2      .1       0
#XS Ineff= 2 , 0
                          197.77         1054.53
Permanent Ineff=
       F       F
Bank Sta=106.6,123.2
XS Rating Curve= 0 ,0
Exp/Cntr(USF)=0,0
Exp/Cntr=0.3,0.1

Type RM Length L Ch R = 1 ,12994   ,282.2,280.3,274.2
XS GIS Cut Line= 4
 1643537.4489893440523.7935179961643581.72143844440535.388683247
1643776.73103583440676.6388781171643880.23295984440693.335395532
#Sta/Elev= 30
       0 1070.79      11 1066.37    19.3 1062.27    27.6  1059.3    35.6 1055.74
    45.4 1050.23    61.4 1039.99    63.5  1038.3    73.4 1028.58    76.9 1027.33
    82.7 1025.96    88.2 1024.28    93.2 1024.07   102.7 1024.37   114.2 1025.93
   119.9 1026.37   127.7 1026.36   132.7 1027.23   142.6 1027.75   162.3 1027.59
   214.4  1028.5   248.8 1030.28     266 1032.96   274.6  1035.2   286.6 1037.48
   318.3  1045.8   334.2 1051.96   342.7 1054.25     371 1059.51   391.4 1062.54
#Mann= 3 ,-1,0
       0      .1       0    82.7    .045       0   114.2      .1       0
Bank Sta=82.7,114.2
XS Rating Curve= 0 ,0
Exp/Cntr(USF)=0,0
Exp/Cntr=0.3,0.1

Type RM Length L Ch R = 1 ,12714   ,501.6,506,503.4
XS GIS Cut Line= 3
 1643404.7982815440772.8135617031643639.04404413440864.169409132
1643771.39290003440946.155426055
#Sta/Elev= 30
       0 1078.24    10.2    1068    29.3 1051.84    42.2 1042.98    54.9 1036.19
      61 1033.62    85.1 1025.23    93.7 1023.45   104.71022.609   110.9 1021.38
   115.2 1021.22   122.8 1021.69     127 1022.56   132.4 1023.89   136.7 1024.34
   162.4 1026.04   183.9 1025.55   226.8 1026.38   239.7 1026.17   257.4 1026.52
   299.7 1028.76   313.5 1028.31   333.8 1029.71   343.3 1030.94   348.4 1031.92
   365.6 1037.97   373.7  1040.2   398.6 1050.66   403.3  1053.2   407.1 1055.72
#Mann= 3 ,-1,0
       0      .1       0   104.7    .045       0     127      .1       0
Bank Sta=104.7,127
XS Rating Curve= 0 ,0
Exp/Cntr(USF)=0,0
Exp/Cntr=0.3,0.1

Type RM Length L Ch R = 1 ,12208   ,385,388.1,389.4
XS GIS Cut Line= 4
1643338.22511521 441148.222067461643418.48474086441220.797260869
1643571.31955992441269.4653317441643631.16609886441295.338817319
#Sta/Elev= 30
       0 1049.45    15.7 1046.51    24.3 1043.97    36.3 1041.35    41.2 1039.69
    51.1 1033.54      61 1025.05    66.7 1022.97      78 1021.56    83.4 1021.41
   125.2 1021.37   147.7 1021.88   164.5 1019.58   171.61016.945   181.3 1016.24
   196.61016.952   202.3 1018.05   220.7 1020.13   236.7 1020.71   240.1 1021.55
   249.4 1025.54   255.8 1029.52   265.2 1038.63   277.6 1048.82   286.9 1055.11
   295.6 1062.99   304.3 1069.95   320.2 1079.49   329.4 1084.09   333.8 1085.52
#Mann= 3 ,-1,0
       0      .1       0   171.6    .045       0   196.6      .1       0
Bank Sta=171.6,196.6
XS Rating Curve= 0 ,0
Exp/Cntr(USF)=0,0
Exp/Cntr=0.3,0.1

Type RM Length L Ch R = 1 ,11820   ,188.8,180.6,172.2
XS GIS Cut Line= 5
1643125.00399906441434.2242546241643171.49007065441468.377286817
1643306.20480875441505.3764050251643358.38305238441542.375523234
1643387.79260787441585.066813475
#Sta/Elev= 30
       0  1047.7      21 1044.51    46.8 1041.25    53.5 1040.53    66.6  1039.9
    74.9 1038.17    79.1 1036.27    83.2 1032.68    91.5 1023.23    95.7  1017.5
    99.8 1013.53   100.6 1013.25     104 1012.31   108.1  1012.1   112.3 1012.13
   118.91013.191   124.7 1014.34   128.8 1014.69   137.1 1014.51   149.6 1016.05
   157.9 1019.16   165.7 1020.71   186.9 1021.87     201 1023.31   206.8 1024.27
   212.5 1025.75   237.4 1033.75   248.8  1036.8   273.7 1041.89   313.2 1050.97
#Mann= 3 ,-1,0
       0      .1       0   100.6    .045       0   118.9      .1       0
Bank Sta=100.6,118.9
XS Rating Curve= 0 ,0
Exp/Cntr(USF)=0,0
Exp/Cntr=0.3,0.1

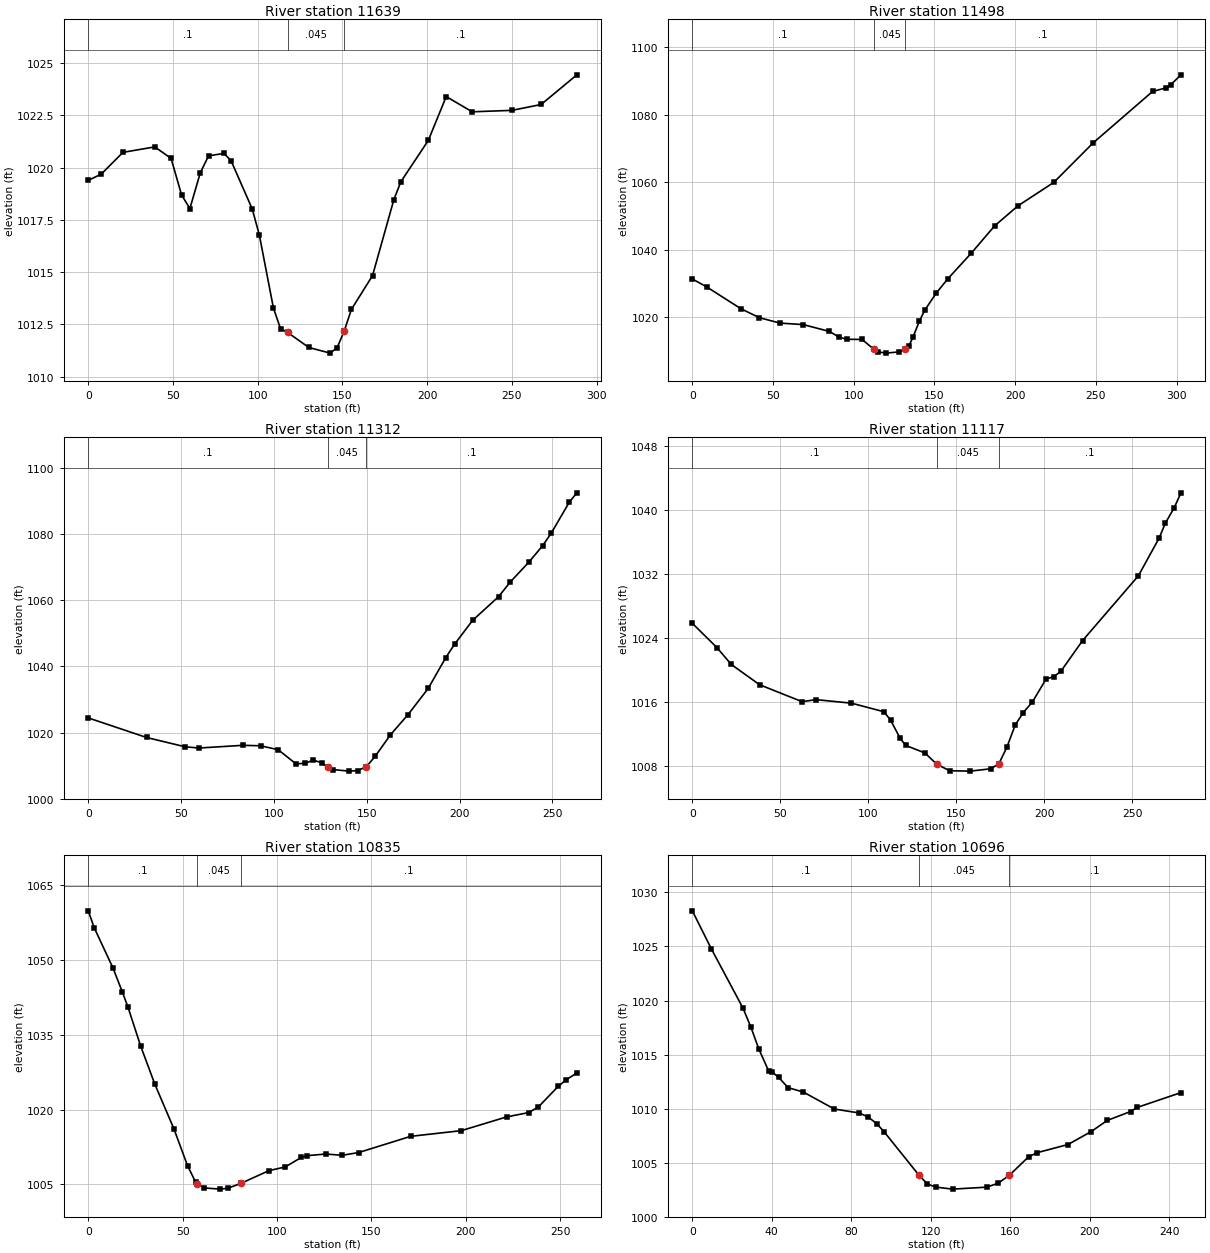
Type RM Length L Ch R = 1 ,11639   ,128.9,140.7,153.8
XS GIS Cut Line= 4
1643092.91689972 441738.257400931643147.78411019441674.756852058
1643269.77960906441637.9736182591643306.08770227441570.042347094
#Sta/Elev= 30
       0 1019.39     7.6 1019.68    20.5 1020.73    39.3 1020.99    48.9 1020.44
    55.1 1018.69      60 1018.04    66.1 1019.74      71 1020.56    80.1 1020.68
    84.3 1020.33    96.8 1018.02     101 1016.77   109.3 1013.28   113.5 1012.29
   117.7 1012.11   130.2 1011.39   142.8 1011.12   146.9 1011.38   151.1 1012.18
   155.3 1013.21   167.8 1014.83   180.4 1018.47   184.5 1019.32   200.7  1021.3
   211.3  1023.4   226.6 1022.67   250.2 1022.74   267.3 1023.02   288.4 1024.44
#Mann= 3 ,-1,0
       0      .1       0   117.7    .045       0   151.1      .1       0
Bank Sta=117.7,151.1
XS Rating Curve= 0 ,0
Exp/Cntr(USF)=0,0
Exp/Cntr=0.3,0.1

Type RM Length L Ch R = 1 ,11498   ,182.7,186.7,190.7
XS GIS Cut Line= 3
1643040.58819478441722.2832998831643208.79187833441834.988306118
1643280.51324593441905.002022113
#Sta/Elev= 30
       0 1031.37     9.1 1028.97    30.1 1022.57    41.6 1019.91    54.4 1018.32
    68.7 1017.88    84.9 1015.86    90.9 1014.18    95.7 1013.54   105.1 1013.49
   112.41010.615     115 1009.83   119.8 1009.44   128.1 1009.81   131.81010.587
   134.2 1011.59   136.8 1014.28   140.6 1018.87   143.9 1022.08   151.2 1027.27
   158.3 1031.45   172.8 1039.01   187.2 1047.06   201.7 1053.01   223.9 1059.94
   248.3 1071.64   285.1 1086.85   293.6 1087.93   296.3 1088.82   302.7 1091.77
#Mann= 3 ,-1,0
       0      .1       0   112.4    .045       0   131.8      .1       0
Bank Sta=112.4,131.8
XS Rating Curve= 0 ,0
Exp/Cntr(USF)=0,0
Exp/Cntr=0.3,0.1

Type RM Length L Ch R = 1 ,11312   ,177.7,194.5,209.1
XS GIS Cut Line= 4
1642946.01532883441777.3370693031642952.33996443441836.367001487
1643029.28969745441956.5350777211643061.96698134442008.186268382
#Sta/Elev= 30
       0 1024.43    31.4 1018.51    52.1 1015.71    59.6 1015.32    83.3 1016.14
    92.8    1016   102.3 1014.82   111.8 1010.58   116.6 1010.66   121.3 1011.67
   125.7 1010.86     1291009.546   131.7 1008.82   140.4 1008.34   145.1  1008.5
   149.8 1009.66   154.6 1012.85   162.8 1019.32   172.3 1025.45   183.1 1033.32
   192.6 1042.66   197.3 1046.68     207 1053.88     221 1061.06   227.3 1065.48
   237.3 1071.48   244.7 1076.44   249.4 1080.27   259.2  1089.7   263.2 1092.46
#Mann= 3 ,-1,0
       0      .1       0     129    .045       0   149.8      .1       0
Bank Sta=129,149.8
XS Rating Curve= 0 ,0
Exp/Cntr(USF)=0,0
Exp/Cntr=0.3,0.1

Type RM Length L Ch R = 1 ,11117   ,299.2,282.6,250.7
XS GIS Cut Line= 5
  1642834.690907441794.4870162861642842.18895802441885.642677662
1642790.03001165441972.9039489671642806.27566986442033.965216015
1642823.04841186442047.115599189
#Sta/Elev= 30
       0 1025.84    14.1 1022.77    22.1 1020.69    38.2 1018.15    62.3 1016.03
    70.3 1016.28    90.4 1015.84   108.8 1014.77   112.6 1013.73   118.1 1011.42
   121.3 1010.54   132.1 1009.61   138.8 1008.21   146.1 1007.38   157.9 1007.33
   169.4 1007.62   174.1 1008.23   178.7 1010.33   183.4 1013.09     188 1014.67
   193.1 1015.96     201 1018.87   205.2 1019.14   209.3 1019.81   221.7 1023.68
   253.4 1031.79   265.2 1036.52   268.8 1038.42   273.7 1040.29   277.6 1042.18
#Mann= 3 ,-1,0
       0      .1       0   138.8    .045       0   174.1      .1       0
Bank Sta=138.8,174.1
XS Rating Curve= 0 ,0
Exp/Cntr(USF)=0,0
Exp/Cntr=0.3,0.1

Type RM Length L Ch R = 1 ,10835   ,150.3,138.3,121
XS GIS Cut Line= 5
1642532.47184138441975.8175570161642557.83046778441988.881091829
1642666.18096242442032.6823556161642725.35109069442051.893436225
1642768.38391125442079.557392301
#Sta/Elev= 30
       0  1059.9     3.2 1056.48    13.1 1048.43    18.1 1043.59    21.1 1040.51
    27.8 1032.72    35.3 1025.08    45.4 1016.12    52.6 1008.73    56.9 1005.42
    57.7 1005.14    61.2 1004.28    69.8 1004.03    74.1 1004.22      81 1005.21
    95.7 1007.74   104.3 1008.48   112.9  1010.4     116 1010.75   125.9 1011.08
   134.5 1010.82   143.2 1011.37   170.8 1014.63   197.6 1015.77   221.6 1018.53
   233.2 1019.39   238.4 1020.52   248.9 1024.65   253.2    1026   258.8 1027.34
#Mann= 3 ,-1,0
       0      .1       0    57.7    .045       0      81      .1       0
Bank Sta=57.7,81
XS Rating Curve= 0 ,0
Exp/Cntr(USF)=0,0
Exp/Cntr=0.3,0.1

Type RM Length L Ch R = 1 ,10696   ,35.4,38.5,45.4
XS GIS Cut Line= 4
1642430.65066406442166.2177209021642469.03802536442167.870978961
1642638.05842217442106.6140815321642661.75467535442091.992989147
#Sta/Elev= 30
       0 1028.29     9.5  1024.8    25.5  1019.3    29.5 1017.53    33.5 1015.51
    38.4  1013.5    40.3 1013.37    43.4 1012.91    48.2 1011.95    55.9 1011.54
    71.5 1009.97      84 1009.61    88.5 1009.24    92.8 1008.62    96.5 1007.88
     114 1003.88   118.3 1003.05   122.5 1002.76     131 1002.57   148.1 1002.75
   153.9 1003.11   159.6 1003.85   169.3 1005.56   173.6 1005.94   189.1 1006.69
   200.8 1007.89   208.9 1008.92   220.6 1009.74   224.1 1010.13     246 1011.49
#Mann= 3 ,-1,0
       0      .1       0     114    .045       0   159.6      .1       0
Bank Sta=114,159.6
XS Rating Curve= 0 ,0
Exp/Cntr(USF)=0,0
Exp/Cntr=0.3,0.1

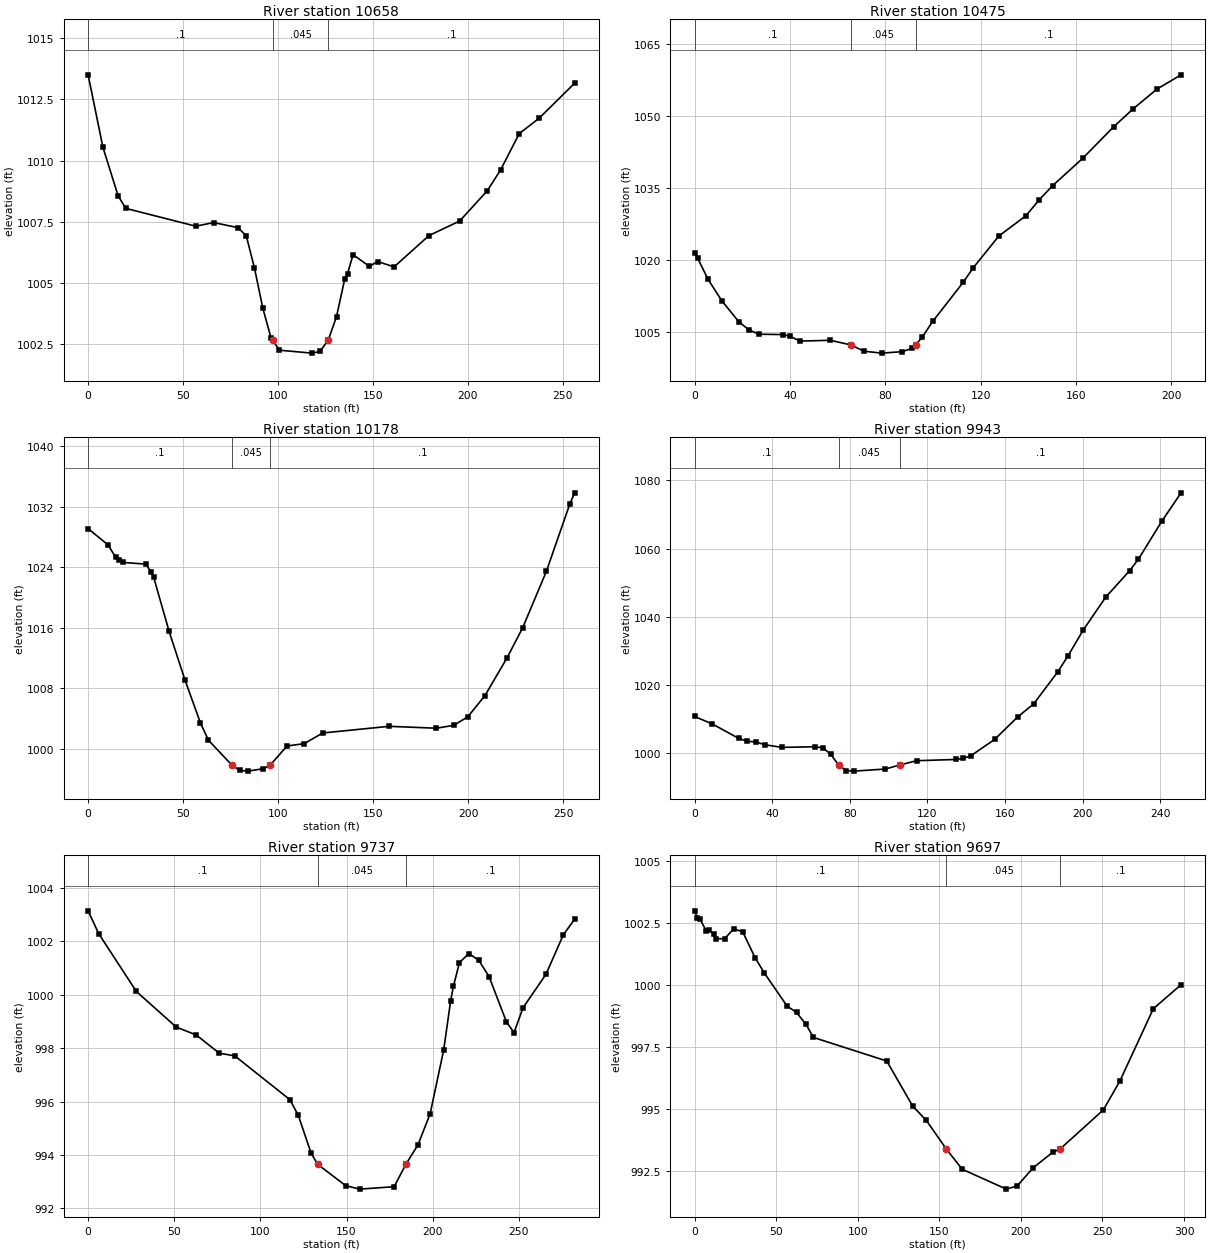
Type RM Length L Ch R = 1 ,10658   ,165.2,182.6,205.3
XS GIS Cut Line= 4
1642440.29565383442198.4505543821642476.31890126442199.716776242
1642653.18369015 442127.789456711642674.35906533442107.622432731
#Sta/Elev= 30
       0  1013.5     7.8 1010.54    15.8 1008.56    19.8 1008.05    56.7 1007.32
    66.1 1007.47      79 1007.26    83.3 1006.92    87.6 1005.61      92 1003.97
    96.3 1002.76    97.11002.687   100.6 1002.26   117.9 1002.14   122.2 1002.21
   126.5 1002.69   130.8 1003.63   135.1 1005.16   136.6 1005.38   139.5 1006.16
   148.1 1005.68   152.4 1005.88   161.1 1005.66   179.5 1006.94   195.6 1007.53
   210.2 1008.77   217.2 1009.62     227  1011.1   237.5 1011.73   256.2 1013.16
#Mann= 3 ,-1,0
       0      .1       0    97.1    .045       0   126.5      .1       0
Bank Sta=97.1,126.5
XS Rating Curve= 0 ,0
Exp/Cntr(USF)=0,0
Exp/Cntr=0.3,0.1

Type RM Length L Ch R = 1 ,10475   ,296.2,297.4,299.1
XS GIS Cut Line= 3
1642393.49422408442215.2773986181642436.06905248442326.196030504
 1642495.9993366442386.816350284
#Sta/Elev= 30
       0 1021.41     1.3 1020.37     5.6 1015.99    11.5 1011.42    18.5 1007.13
    22.8 1005.37    27.1 1004.48    37.1  1004.4    39.9 1004.08    44.2 1003.04
      57 1003.21    65.6 1002.24    71.1 1000.93    78.5 1000.53      87 1000.83
    91.3 1001.52    92.8 1002.25    95.6 1003.93    99.9 1007.14   112.7 1015.31
     117  1018.4   127.7    1025     139  1029.2   144.6 1032.53   150.2 1035.48
   162.9 1041.22   175.8 1047.77     184 1051.52     194 1055.65   204.1 1058.62
#Mann= 3 ,-1,0
       0      .1       0    65.6    .045       0    92.8      .1       0
Bank Sta=65.6,92.8
XS Rating Curve= 0 ,0
Exp/Cntr(USF)=0,0
Exp/Cntr=0.3,0.1

Type RM Length L Ch R = 1 ,10178   ,233.1,235.2,237.7
XS GIS Cut Line= 4
1642127.33498608442286.0353325821642125.26018937442327.531266696
1642157.76533776442452.0190690381642179.20490372442535.010937266
#Sta/Elev= 30
       0  1029.1    10.5 1026.94    14.5  1025.3    16.1 1025.02    18.5 1024.63
    30.5 1024.41      33 1023.38    34.5 1022.65    42.6 1015.52    50.9 1009.13
    59.1 1003.41    63.3 1001.14    75.7  997.83    79.8  997.16    83.9  997.06
    92.2  997.38    95.6997.8038   104.6 1000.38   113.6 1000.69   123.4  1002.1
   158.3 1002.98   183.1 1002.73   192.3 1003.11   199.7 1004.24   208.7 1007.04
   220.3 1012.01   228.6 1016.03     241 1023.45   253.4  1032.4   255.9 1033.83
#Mann= 3 ,-1,0
       0      .1       0    75.7    .045       0    95.6      .1       0
Bank Sta=75.7,95.6
XS Rating Curve= 0 ,0
Exp/Cntr(USF)=0,0
Exp/Cntr=0.3,0.1

Type RM Length L Ch R = 1 ,9943    ,171.6,206.3,227.7
XS GIS Cut Line= 4
1641928.16757585442336.2067211861641903.57739267442385.387087544
1641914.33559781442501.422014418 1641895.1245172442578.266336852
#Sta/Elev= 30
       0 1010.83     9.2 1008.63    22.7 1004.43    27.2 1003.57    31.7 1003.38
    36.1 1002.56    45.1 1001.78    62.2 1001.97    66.2 1001.63    70.2  999.76
    74.2  996.64    78.2  994.97    82.3  994.83    98.3  995.45   105.8996.6339
   114.4  997.88   134.5  998.24   138.5  998.54   142.5  999.38   154.6 1004.09
   166.6 1010.75   174.7 1014.48   187.1 1023.84   192.4 1028.53   200.2 1036.06
   211.8  1045.7   224.2 1053.52   228.7 1056.85   240.7 1067.92   250.7  1076.3
#Mann= 3 ,-1,0
       0      .1       0    74.2    .045       0   105.8      .1       0
Bank Sta=74.2,105.8
XS Rating Curve= 0 ,0
Exp/Cntr(USF)=0,0
Exp/Cntr=0.3,0.1

Type RM Length L Ch R = 1 ,9737    ,39.4,39.8,54.6
XS GIS Cut Line= 5
1641852.53405411442357.5529858761641797.07473817442409.651131155
1641746.09698311442411.8919115971641627.89581479442433.179325797
1641608.42992553442462.517317628
#Sta/Elev= 30
       0 1003.14     6.1 1002.29      28 1000.12    51.1  998.79    62.8  998.49
    76.1  997.81    85.1  997.71   117.1  996.07     122  995.48   129.4  994.07
   133.2  993.65   149.5  992.85   157.6  992.72   177.6  992.81   184.5  993.66
   191.4  994.37   198.5  995.54   206.4  997.94   210.4  999.77     212 1000.31
   215.5  1001.2     221 1001.54   226.7 1001.29   232.7 1000.68   242.8  998.98
   247.2  998.58   252.4  999.51   265.7 1000.76   275.8 1002.24   282.4 1002.83
#Mann= 3 ,-1,0
       0      .1       0   133.2    .045       0   184.5      .1       0
Bank Sta=133.2,184.5
XS Rating Curve= 0 ,0
Exp/Cntr(USF)=0,0
Exp/Cntr=0.3,0.1

Type RM Length L Ch R = 1 ,9697    ,143.4,110.2,71.7
XS GIS Cut Line= 5
1641837.40878613 442341.307327671641784.75044574442391.724887618
1641739.93483689442389.4841071761641609.96957125442416.933667592
1641587.54689872442458.929869443
#Sta/Elev= 30
       0 1002.98     1.8 1002.69     3.2 1002.66     7.3 1002.16     8.9  1002.2
    11.7 1002.04    12.9 1001.86    18.4 1001.85    23.9 1002.25    29.5 1002.14
    37.1 1001.09    42.8 1000.47    56.7  999.14    62.5  998.88    68.3   998.4
    72.9  997.87   117.8  996.92   133.7   995.1   142.1  994.52   154.4  993.36
   164.1  992.55   191.1  991.75   197.8  991.88   207.5  992.61   219.8  993.25
   223.9  993.36   250.6  994.95   260.6   996.1   281.2  999.03   298.2    1000
#Mann= 3 ,-1,0
       0      .1       0   154.4    .045       0   223.9      .1       0
Bank Sta=154.4,223.9
XS Rating Curve= 0 ,0
Exp/Cntr(USF)=0,0
Exp/Cntr=0.3,0.1