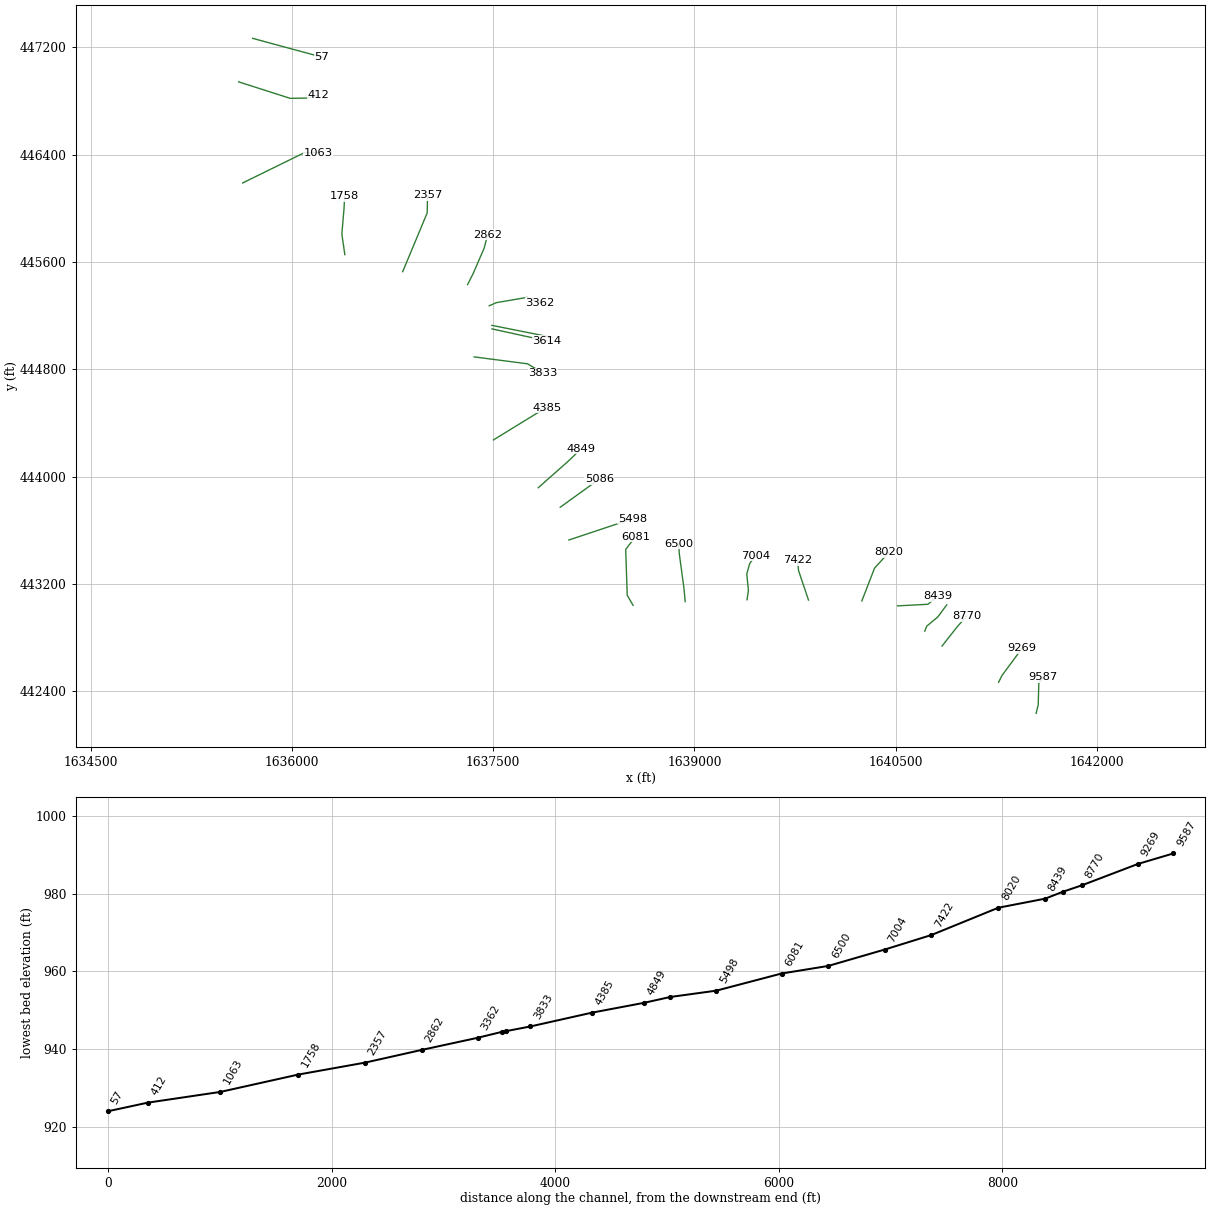
HEC-RAS study LYNNCMPRN.prj: LYNNCMPRN

--- LYNNCMPRN.g01 (geometry) --- (continued)

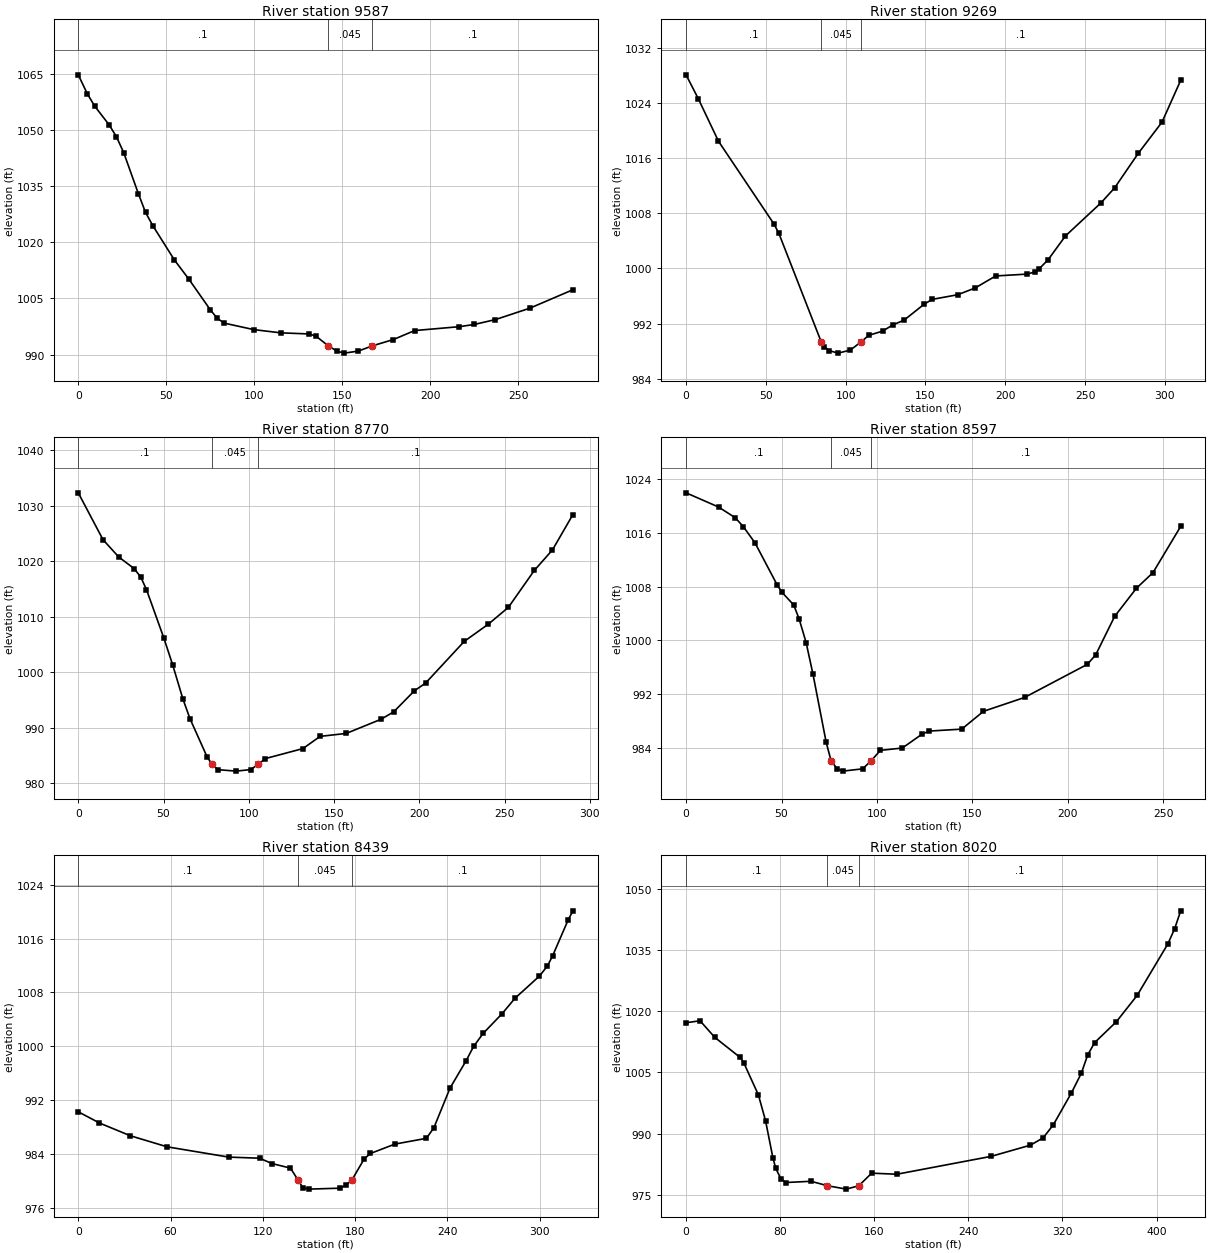
Type RM Length L Ch R = 1 ,9587    ,321.7,317.4,306.2
XS GIS Cut Line= 4
1641546.85602617442235.4429969511641562.37455112442299.150625702
1641566.86675571442458.4196975791641596.67865891442505.792036907
#Sta/Elev= 30
       0 1064.66     5.2 1059.54     9.4 1056.26    17.6 1051.27    21.7 1048.12
    25.8 1043.91    34.1 1032.99    38.2 1027.96    42.3 1024.44    54.6 1015.26
    62.9 1010.08      75 1001.96      79  999.65      83   998.4    99.7  996.68
     115  995.82     131  995.53     135  994.94   141.9992.3837     147  990.92
     151  990.41     159  990.95     167  992.35     179  994.04     191  996.43
   216.5  997.47   224.9  998.06   236.9  999.36   256.4 1002.39   280.9 1007.32
#Mann= 3 ,-1,0
       0      .1       0   141.9    .045       0     167      .1       0
Bank Sta=141.9,167
XS Rating Curve= 0 ,0
Exp/Cntr(USF)=0,0
Exp/Cntr=0.3,0.1

Type RM Length L Ch R = 1 ,9269    ,498.8,499,497.5
XS GIS Cut Line= 4
1641266.92154454442467.5417386151641292.53631869442517.917461099
1641377.06507336442632.3301189441641442.80966033 442721.98182845
#Sta/Elev= 30
       0 1028.12     7.6 1024.68    20.3 1018.48      55 1006.48    58.1 1005.12
    84.6  989.38    86.7  988.66    89.5  988.07    95.3   987.7   102.9  988.14
   109.7  989.34   114.5  990.29   123.1  990.89   129.6  991.81   136.6  992.49
   149.3  994.83   154.3  995.51   170.2  996.18   181.1  997.16     194  998.91
   213.9  999.18   218.9  999.53   221.1  999.92   226.8 1001.25   237.7 1004.72
     260 1009.53   268.5  1011.7   283.3 1016.71   298.2 1021.25   309.9 1027.32
#Mann= 3 ,-1,0
       0      .1       0    84.6    .045       0   109.7      .1       0
Bank Sta=84.6,109.7
XS Rating Curve= 0 ,0
Exp/Cntr(USF)=0,0
Exp/Cntr=0.3,0.1

Type RM Length L Ch R = 1 ,8770    ,175.1,172.9,170.7
XS GIS Cut Line= 3
1640845.43201314 442737.117239241640955.05903005442876.259222247
1641028.84644528442961.641802728
#Sta/Elev= 30
       0 1032.35    14.5 1023.91    23.7  1020.8    32.8 1018.69    36.7 1017.14
      40 1014.91    50.2 1006.17    55.3 1001.41    61.3  995.26    65.5  991.66
    75.6  984.74    78.4  983.47    81.9  982.48    92.6  982.22   101.1   982.5
   105.6983.4636   109.7  984.48   131.7  986.28   141.8  988.48   157.1  989.01
   177.5  991.56   184.9  992.89   197.1   996.7   203.6  998.07   226.3 1005.59
   240.5 1008.71   252.2 1011.73   267.4 1018.38     278 1022.06     290 1028.43
#Mann= 3 ,-1,0
       0      .1       0    78.4    .045       0   105.6      .1       0
Bank Sta=78.4,105.6
XS Rating Curve= 0 ,0
Exp/Cntr(USF)=0,0
Exp/Cntr=0.3,0.1

Type RM Length L Ch R = 1 ,8597    ,170,158.7,149.7
XS GIS Cut Line= 4
1640716.80672789442848.7513909711640732.03270246442886.230712993
1640814.01871938442954.1619841581640880.77876174443044.346602774
#Sta/Elev= 30
       0 1021.94      17 1019.83    25.7 1018.25      30 1016.91    36.1  1014.5
    47.8  1008.2    50.3 1007.12    56.4 1005.25    59.2  1003.2    62.9  999.65
    66.5  994.93    73.4  984.81      76  982.04    79.1   980.9    82.1  980.53
    92.5  980.87    96.8982.0231   101.8  983.62   113.3  983.97   123.7  986.05
   127.4  986.49   144.4  986.78   155.8  989.43   177.3  991.49   210.2  996.42
   214.6  997.84   224.5 1003.55   235.9 1007.74   244.6 1010.07   259.1 1016.94
#Mann= 3 ,-1,0
       0      .1       0      76    .045       0    96.8      .1       0
Bank Sta=76,96.8
XS Rating Curve= 0 ,0
Exp/Cntr(USF)=0,0
Exp/Cntr=0.3,0.1

Type RM Length L Ch R = 1 ,8439    ,396.8,418.3,433.4
XS GIS Cut Line= 3
1640514.34568622443036.7740211741640740.39284716443048.486309305
 1640812.7378708443110.593550181
#Sta/Elev= 30
       0  990.25    13.8  988.58    33.8  986.69    57.8  985.04    97.9  983.51
   117.9  983.35   125.9  982.56     138  981.87   142.8980.1633     146  978.99
     150  978.75     170  978.89     174  979.31     178  980.12     186  983.26
     190  984.05     206  985.45   226.4   986.3   231.3  987.88   241.8  993.78
   252.3  997.86   257.1  999.96   263.3  1001.9   275.6 1004.82     284 1007.12
   299.8  1010.4   305.1 1011.91   308.5 1013.43   318.5 1018.72   321.7 1020.13
#Mann= 3 ,-1,0
       0      .1       0   142.8    .045       0     178      .1       0
Bank Sta=142.8,178
XS Rating Curve= 0 ,0
Exp/Cntr(USF)=0,0
Exp/Cntr=0.3,0.1

Type RM Length L Ch R = 1 ,8020    ,581.2,598.6,600.9
XS GIS Cut Line= 3
1640247.68110387 443073.452718791640342.55063774443318.005294984
1640449.01533685443435.011053422
#Sta/Elev= 30
       0 1017.17    11.9 1017.65    24.4 1013.59      46 1008.67    49.1 1007.34
    61.5  999.49    67.6  993.14    73.8  984.12    76.2  981.56    80.5     979
    84.8  978.04   106.3  978.34   120.2  977.25   136.3  976.42   146.9977.2584
   157.8  980.33   179.2  980.07   259.3  984.44   292.8  987.19   303.6  988.99
   312.2  992.16   327.5  999.92     336 1004.78   341.4 1009.24   347.3 1012.29
   365.7 1017.38   383.5 1023.87   409.6 1036.48   415.3 1040.14   420.5 1044.58
#Mann= 3 ,-1,0
       0      .1       0   120.2    .045       0   146.9      .1       0
Bank Sta=120.2,146.9
XS Rating Curve= 0 ,0
Exp/Cntr(USF)=0,0
Exp/Cntr=0.3,0.1

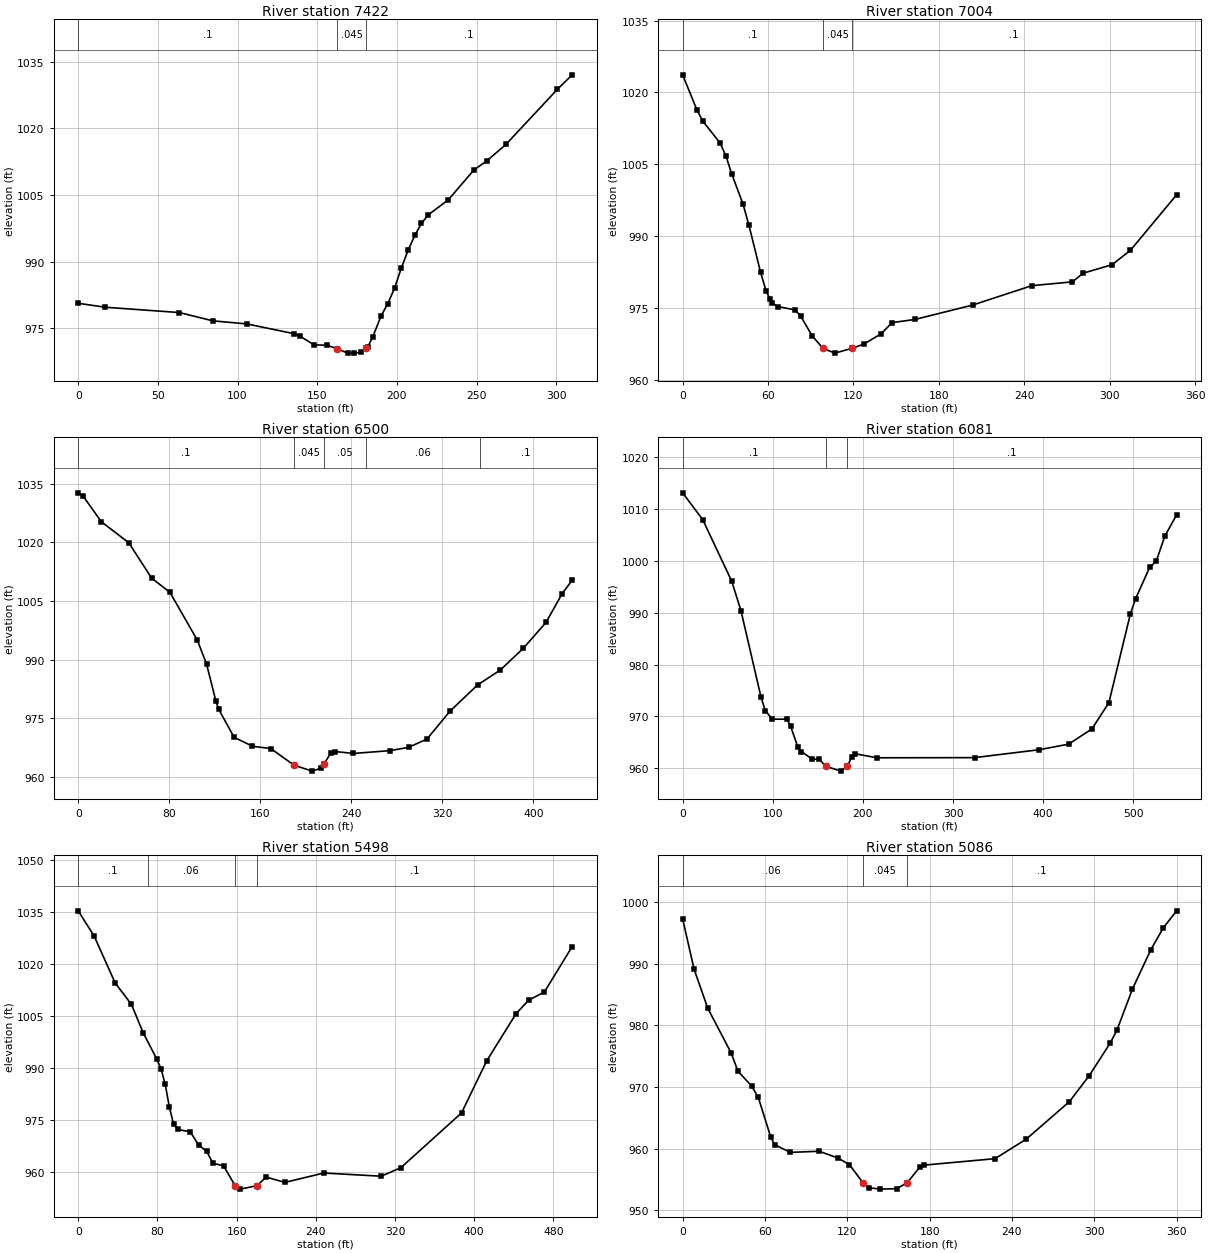
Type RM Length L Ch R = 1 ,7422    ,418.4,417.5,414.3
XS GIS Cut Line= 3
1639849.94891573443080.413882016 1639776.1615005443299.433670082
1639767.96289881443377.906000566
#Sta/Elev= 30
       0  980.61      17  979.72    63.4  978.53    84.5  976.66   105.7  975.97
   135.2  973.79   139.4  973.16   147.9  971.27   156.3  971.15   162.6  970.37
     169   969.4   173.2  969.39   177.4  969.57   180.7970.4445   181.6  970.71
   184.7  972.92   190.1  977.78   194.3  980.56   198.5  983.99   202.7   988.5
     207  992.55   211.2  995.88   215.4  998.59   219.6 1000.51   232.2 1003.89
   248.3 1010.63   256.4 1012.68   268.4 1016.38   300.6 1028.76     310 1032.06
#Mann= 3 ,-1,0
       0      .1       0   162.6    .045       0   180.7      .1       0
Bank Sta=162.6,180.7
XS Rating Curve= 0 ,0
Exp/Cntr(USF)=0,0
Exp/Cntr=0.3,0.1

Type RM Length L Ch R = 1 ,7004    ,502.6,504.6,505.4
XS GIS Cut Line= 5
1639391.80137058443082.5471215091639402.51219649443150.382352269
1639390.18206024443274.3603381131639411.69847052 443351.97310377
1639454.73129108443411.143232044
#Sta/Elev= 30
       0 1023.68    10.1 1016.32    14.2 1014.01    26.3 1009.47    30.4 1006.77
    34.4 1003.08    42.5  996.65    46.6  992.29    54.7  982.56    58.7  978.54
    61.5  976.86    62.8  976.12    66.8  975.36    78.9  974.67    82.9  973.38
    90.9   969.3    98.6966.6368     107  965.65   118.9 966.652   127.1  967.51
   139.2  969.63   147.2  972.01   163.3  972.68   203.8  975.68   245.3  979.72
   273.8  980.51   281.3  982.31   301.7  984.09   314.6   987.1     347  998.66
#Mann= 3 ,-1,0
       0      .1       0    98.6    .045       0   118.9      .1       0
Bank Sta=98.6,118.9
XS Rating Curve= 0 ,0
Exp/Cntr(USF)=0,0
Exp/Cntr=0.3,0.1

Type RM Length L Ch R = 1 ,6500    ,419.4,418.7,417.1
XS GIS Cut Line= 4
1638931.12700992443068.3058204621638922.69416246443161.067142467
1638887.90866671443420.3772017071638881.58403112443499.435146598
#Sta/Elev= 30
       0 1032.72     4.2 1031.92    20.3 1025.31    44.4 1019.94    64.5 1010.87
    80.6 1007.22   104.7  994.96   112.8  988.83   120.9  979.45   123.4  977.28
     137  970.09   153.1  967.81   169.3   967.2   189.5  962.97   205.6  961.43
   213.7  962.21     216  963.26   221.8  965.97   225.8  966.44   241.9  965.96
   274.2  966.68   290.4  967.53   306.5  969.66   326.7  976.78   350.9   983.5
     371  987.34   391.1  992.88   411.1  999.52   425.3 1006.91   434.1 1010.33
#Mann= 5 ,-1,0
       0      .1       0   189.5    .045       0     216     .05       0
  253.14     .06       0  353.14      .1       0
Bank Sta=189.5,216
XS Rating Curve= 0 ,0
Exp/Cntr(USF)=0,0
Exp/Cntr=0.3,0.1

Type RM Length L Ch R = 1 ,6081    ,593.6,582.8,561.9
XS GIS Cut Line= 4
1638542.59314684443040.5195697711638499.21430191443115.709567655
1638487.64660993443456.9564811271638559.94468481 443552.38993998
#Sta/Elev= 30
       0  1013.1    22.3 1007.93    54.5  996.05    64.7  990.39    86.8  973.84
    91.6  971.14    99.6  969.48   115.7  969.48   119.7  968.17   127.7  964.15
   131.7  963.24   143.7   961.8   151.7  961.73   158.7960.4075   175.7  959.47
   182.7960.4175   187.7   962.2   191.7   962.8   215.7  962.04   323.8  962.07
   395.8   963.6   428.2  964.67     454  967.59   472.9  972.66   496.8  989.82
   502.5  992.69   518.1  998.73   525.4  999.92     535 1004.78     548 1008.84
#Mann= 3 ,-1,0
       0      .1       0   158.7    .045       0   182.7      .1       0
Bank Sta=158.7,182.7
XS Rating Curve= 0 ,0
Exp/Cntr(USF)=0,0
Exp/Cntr=0.3,0.1

Type RM Length L Ch R = 1 ,5498    ,405.4,411.9,408.4
XS GIS Cut Line= 3
 1638064.7435333443527.8182915621638455.68867899443658.133340126
1638537.80501096443686.695542551
#Sta/Elev= 30
       0 1035.38    16.2 1028.02    37.3 1014.56    53.8 1008.36    65.5 1000.24
    79.4  992.56    83.7  989.73    87.9  985.28    92.1  978.68    96.3  973.81
   100.5  972.28   113.2  971.59   121.6  967.76   129.7     966     136  962.57
   146.9  961.75   158.4956.0986   163.8  955.06   180.6  956.06   189.8  958.54
   208.8     957   248.1  959.71   305.9  958.79   325.8  961.21   387.2  977.05
   412.5  992.01   442.2 1005.65   454.9 1009.58   470.9 1011.95     499 1025.07
#Mann= 4 ,-1,0
       0      .1       0      70     .06       0   158.4    .045       0
   180.6      .1       0
Bank Sta=158.4,180.6
XS Rating Curve= 0 ,0
Exp/Cntr(USF)=0,0
Exp/Cntr=0.3,0.1

Type RM Length L Ch R = 1 ,5086    ,237.5,237.3,240.6
XS GIS Cut Line= 2
1637999.39979359443771.6569471511638291.40821883443982.210390615
#Sta/Elev= 30
       0  997.24     8.3  989.12    18.3  982.76    35.4  975.49    40.3  972.54
    50.2  970.17    55.1  968.32    64.2  961.88      67  960.64    78.5  959.39
    99.5  959.57   112.9   958.5   121.5  957.42   131.4  954.47   135.8  953.66
   143.9  953.43   155.9   953.5   163.6  954.45   173.1  957.07   175.9  957.32
   227.7  958.37   250.4  961.53   281.9  967.62   296.3  971.82   311.6   977.1
   316.5  979.19   327.8  985.85   341.1  992.19   350.3  995.79     360  998.55
#Mann= 3 ,-1,0
       0     .06       0   131.4    .045       0   163.6      .1       0
Bank Sta=131.4,163.6
XS Rating Curve= 0 ,0
Exp/Cntr(USF)=0,0
Exp/Cntr=0.3,0.1

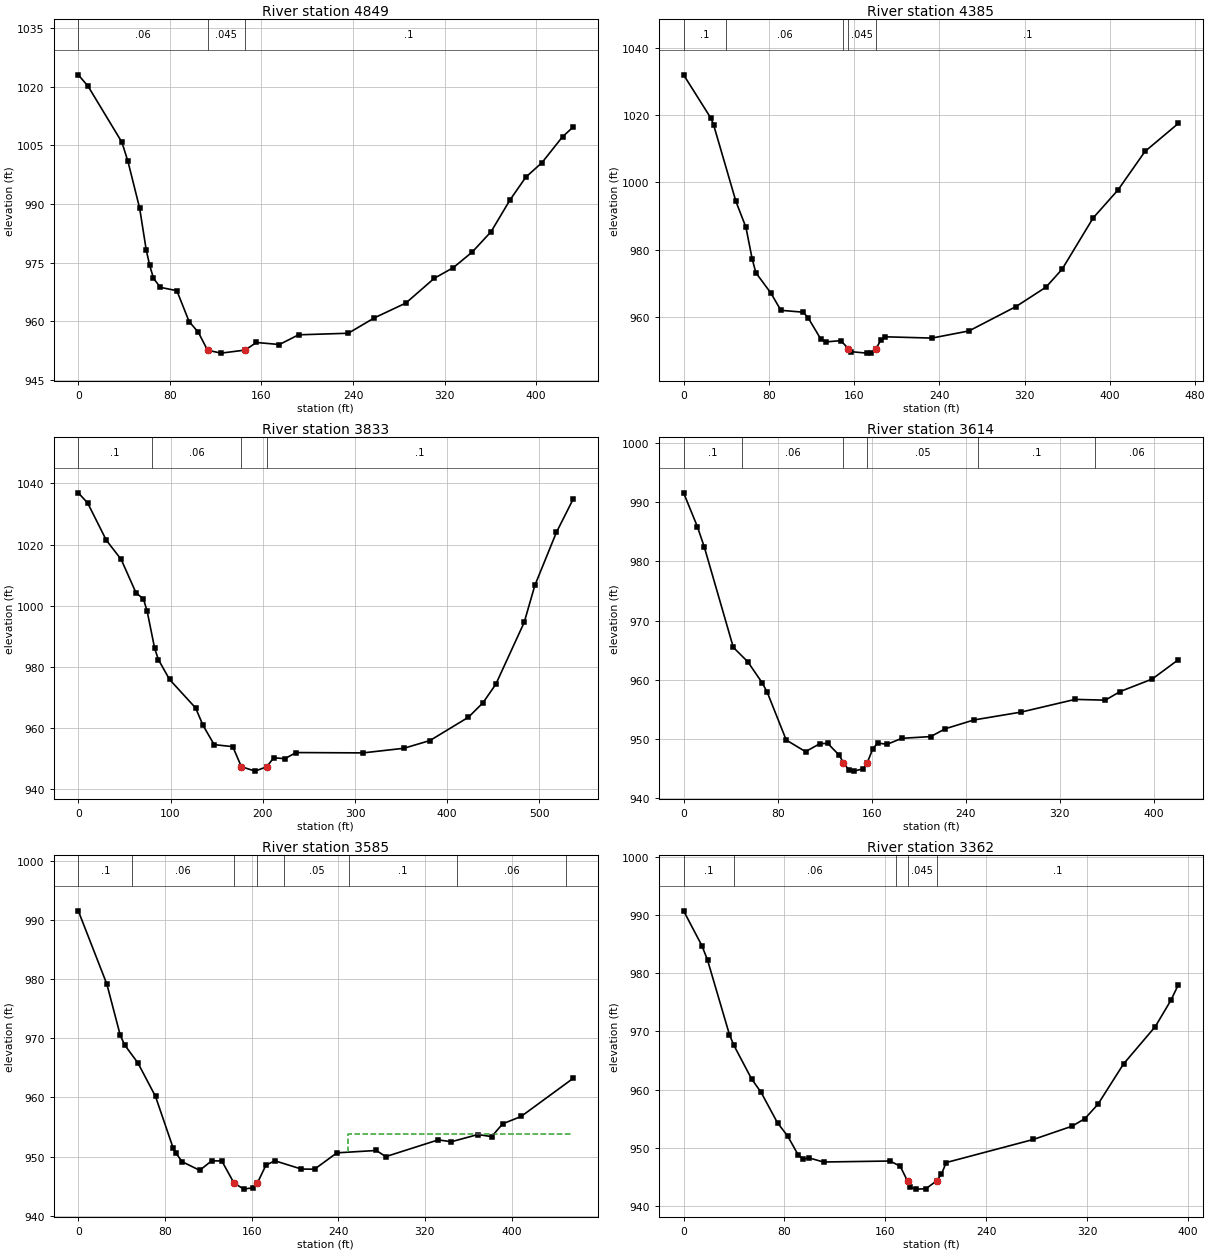
Type RM Length L Ch R = 1 ,4849    ,466,463.6,461.3
XS GIS Cut Line= 3
1637835.62506593443916.9810723961638056.98731162444113.044775724
1638156.07326921444206.860203661
#Sta/Elev= 30
       0 1023.04     8.5 1020.14    38.1 1005.81    43.4 1000.89    53.6  988.96
    59.4   978.2    62.4  974.33    65.7  971.03    71.7  968.72    86.1  967.87
    96.8  959.99   104.9  957.22   112.9  952.66   124.7  951.91   145.7952.6852
   155.6  954.63   175.7  954.11   192.4  956.59   235.8  956.99   258.7  960.93
   286.2  964.72     311  971.04   327.6  973.76   344.1  977.74   360.6  982.95
   377.1  991.05   390.9  996.87   405.1 1000.61     423 1007.21   432.2 1009.67
#Mann= 3 ,-1,0
       0     .06       0   112.9    .045       0   145.7      .1       0
Bank Sta=112.9,145.7
XS Rating Curve= 0 ,0
Exp/Cntr(USF)=0,0
Exp/Cntr=0.3,0.1

Type RM Length L Ch R = 1 ,4385    ,562.3,551.8,544.4
XS GIS Cut Line= 3
1637502.29923268444273.8546326031637822.43510828444470.360800149
1637899.21566382444514.607221981
#Sta/Elev= 30
       0  1031.9    25.6 1019.06    28.1 1017.14    49.1  994.38    58.5  986.69
    64.3  977.43    67.8  973.24    81.9   967.2    91.3  962.08   112.2  961.53
   116.7  959.95   128.9  953.49   133.5  952.71   147.6   953.1   154.5  950.73
   157.4  949.81     172  949.39   175.8  949.45   180.7  950.75   185.2  953.33
   189.4  954.23     233  953.85   267.9  955.98   311.9  963.19   340.1  968.96
   355.2  974.26   384.3  989.45   407.7  997.78     433 1009.19   464.3  1017.5
#Mann= 5 ,-1,0
       0      .1       0      40     .06       0     150      .1       0
   154.5    .045       0   180.7      .1       0
Bank Sta=154.5,180.7
XS Rating Curve= 0 ,0
Exp/Cntr(USF)=0,0
Exp/Cntr=0.3,0.1

Type RM Length L Ch R = 1 ,3833    ,222.6,219.9,218.7
XS GIS Cut Line= 3
 1637358.0134985444892.4107793281637756.69424069444840.840136061
 1637871.7364449444771.418116278
#Sta/Elev= 30
       0 1036.93    10.2 1033.58    30.4 1021.41    46.5 1015.13    62.6 1004.18
    70.7 1002.17    74.7  998.11    82.8  986.04    86.8  982.37    98.9  975.85
   127.2  966.51   135.2  960.84   147.3   954.5   167.5  953.84   176.8  947.28
   191.7  945.83   204.3  947.26   211.9   950.2     224  949.91   236.1  951.91
   308.7   951.8     353  953.31   381.3  955.85     423  963.48   438.7  968.19
   452.7  974.29   483.4   994.5     495 1006.64   518.3 1023.95   536.4  1034.8
#Mann= 4 ,-1,0
       0      .1       0      80     .06       0   176.8    .045       0
   204.3      .1       0
Bank Sta=176.8,204.3
XS Rating Curve= 0 ,0
Exp/Cntr(USF)=0,0
Exp/Cntr=0.3,0.1

Type RM Length L Ch R = 1 ,3614    ,28.2,28.5,28.8
XS GIS Cut Line= 2
1637490.80010649445101.162673306 1637901.9172315 445011.25481606
#Sta/Elev= 30
       0  991.59    11.7   985.9    17.7  982.39    42.3   965.5    54.6  963.07
    66.9   959.5      71  957.99    87.3  949.86   103.7   947.9     116  949.25
   122.6  949.29   132.4  947.29     136     946   140.6  944.81   144.7  944.61
   152.8     945   156.2  946.03     161  948.41   165.1  949.36     173  949.13
   185.6  950.15   210.2  950.44   222.5  951.76     247  953.25   287.2  954.58
     333  956.72   358.7  956.59   371.2  958.04   398.5  960.15   420.8  963.42
#Mann= 6 ,-1,0
       0      .1       0      50     .06       0     136    .045       0
   156.2     .05       0     250      .1       0     350     .06       0
Bank Sta=136,156.2
XS Rating Curve= 0 ,0
Exp/Cntr(USF)=0,0
Exp/Cntr=0.3,0.1

Type RM Length L Ch R = 1 ,3585    ,219.2,223.1,227.3
XS GIS Cut Line= 2
1637490.20419878445127.3904109851637938.20659856445038.250996964
#Sta/Elev= 30
       0  991.57    26.4  979.16    38.7  970.55    42.7   968.9      55  965.85
    71.3  960.16    87.6  951.43    90.4  950.51    95.9  949.12   112.1  947.66
   123.1  949.26   132.5  949.25   143.7945.5242   152.8  944.48     161  944.71
   165.3 945.483   173.2  948.52   181.4  949.28   205.9  947.88   218.1  947.85
   238.8  950.62   275.2  951.02   283.9  949.98   332.3  952.81   344.5   952.5
     369  953.72   381.6  953.36   391.8  955.53   408.8  956.77   456.8  963.21
#Mann= 8 ,-1,0
       0      .1       0      50     .06       0   143.7    .045       0
   165.3      .1       0     190     .05       0     250      .1       0
     350     .06       0     450      .1       0
#XS Ineff= 2 , 0
                          248.71          953.86
Permanent Ineff=
       F       F
Bank Sta=143.7,165.3
XS Rating Curve= 0 ,0
Exp/Cntr(USF)=0,0
Exp/Cntr=0.3,0.1

Type RM Length L Ch R = 1 ,3362    ,488.6,499.8,510.5
XS GIS Cut Line= 4
1637470.74068364 445273.406181511637524.09666291445296.830757774
1637751.83559881445335.8717182141637846.83526921445295.529392426
#Sta/Elev= 30
       0  990.73    14.6  984.71      19  982.27    36.4  969.44    39.8  967.66
    53.9  961.86    61.5  959.53    74.5   954.3    82.6  952.02    90.8  948.83
    94.8  948.06    99.6  948.27     111  947.57   163.8  947.74   171.9  946.83
   177.7944.2679     180  943.25   184.1  942.91   192.2  942.97   200.7  944.33
   204.4  945.44   208.4  947.48   277.4  951.44   308.1  953.72   318.3  955.01
   328.7  957.49     349  964.42   374.2  970.84   386.6  975.36   392.5  978.05
#Mann= 5 ,-1,0
       0      .1       0      40     .06       0  168.27      .1       0
   177.7    .045       0   200.7      .1       0
Bank Sta=177.7,200.7
XS Rating Curve= 0 ,0
Exp/Cntr(USF)=0,0
Exp/Cntr=0.3,0.1

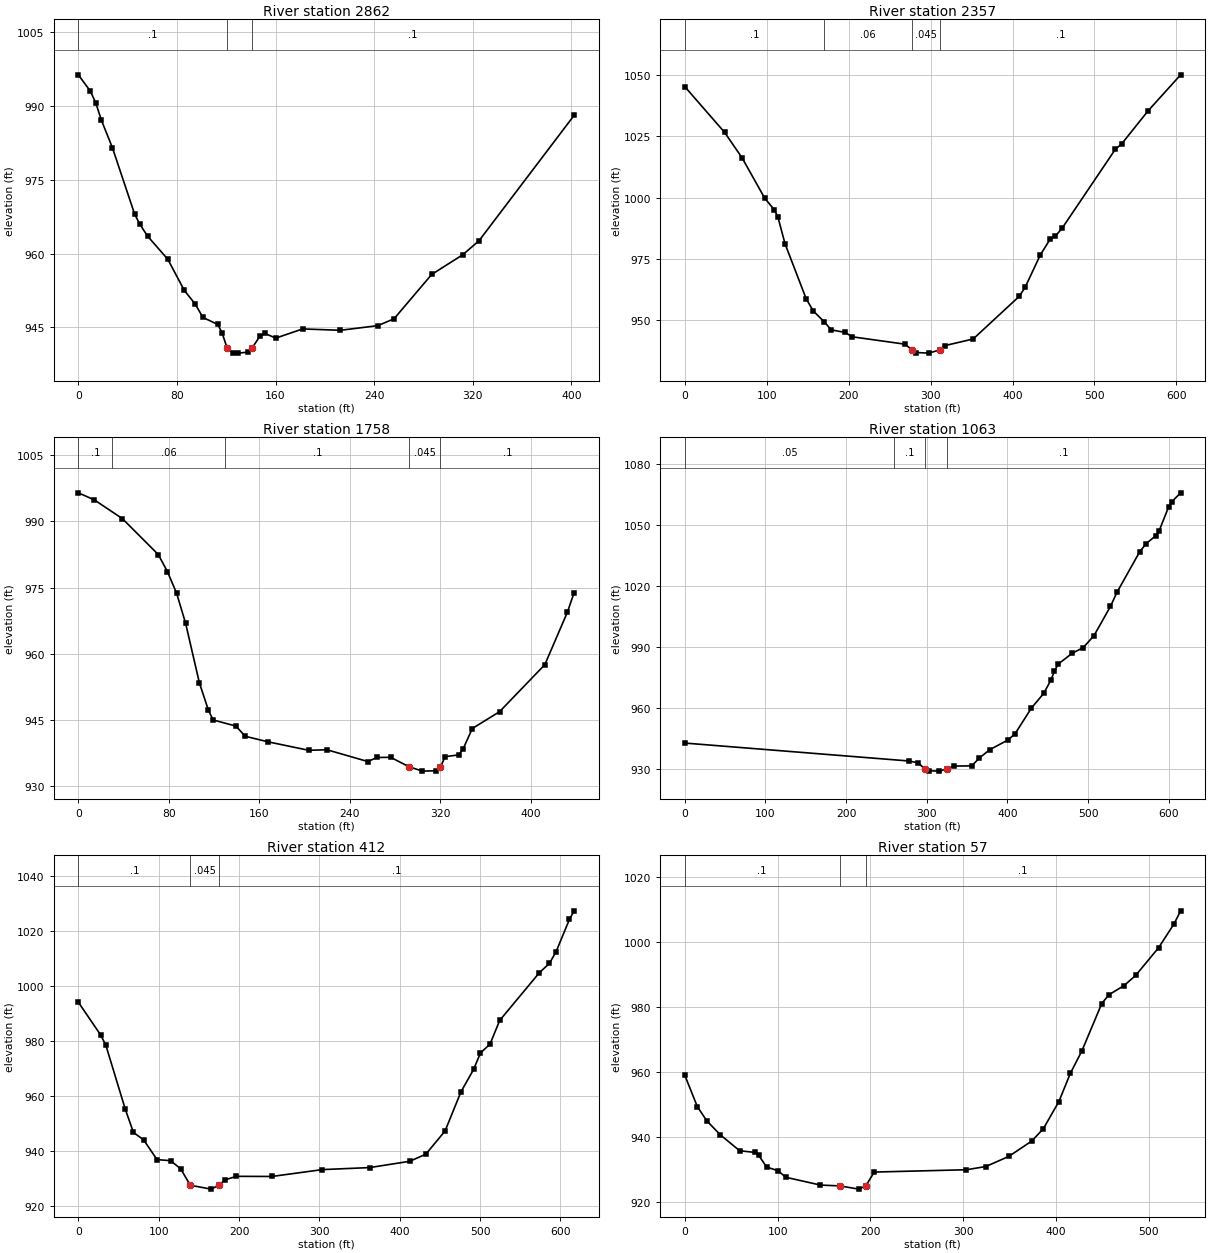
Type RM Length L Ch R = 1 ,2862    ,503.8,504.8,505.4
XS GIS Cut Line= 4
1637309.28941402445431.8152246121637350.39954537445512.981381367
1637432.61980805445702.7204491041637458.97245635445803.914618563
#Sta/Elev= 30
       0  996.35     9.8  993.02    14.3  990.53    18.7  987.14    27.7   981.5
    45.6   968.1    49.7  966.06    56.2  963.56    72.6  958.86      86  952.53
    94.9  949.73   101.1  947.04   113.2  945.61   116.7  943.85   120.7940.8518
   125.4  939.81   129.7  939.79   137.6  939.99     141940.8445   147.2  943.18
   151.5  943.78   160.2  942.84     182  944.71   212.6  944.43   243.1  945.38
   256.2  946.78   286.7  955.78     312   959.8   325.1  962.63   402.3  988.12
#Mann= 3 ,-1,0
       0      .1       0   120.7    .045       0     141      .1       0
Bank Sta=120.7,141
XS Rating Curve= 0 ,0
Exp/Cntr(USF)=0,0
Exp/Cntr=0.3,0.1

Type RM Length L Ch R = 1 ,2357    ,594.7,599.6,603.6
XS GIS Cut Line= 3
1636825.47694719445527.6361654241637008.39845964445966.207020562
1637010.60233328446096.235565552
#Sta/Elev= 30
       0 1045.26    48.6 1026.61      70 1016.16    97.5  999.79   109.3  994.97
   113.7  992.01   122.3   981.2   148.3  958.57     157  953.67     170  949.37
   178.7  946.03   195.4     945   204.6  943.18   268.8  940.18     277  937.93
   282.7  936.77   297.8  936.53   311.6  937.88   317.7  939.62     352   942.3
   408.4  959.76   415.6  963.53   433.9  976.56   446.2  983.19   452.3  984.29
   460.4  987.42   525.5 1019.69   533.5 1022.02   565.5 1035.41   605.2 1050.09
#Mann= 4 ,-1,0
       0      .1       0     170     .06       0     277    .045       0
   311.6      .1       0
Bank Sta=277,311.6
XS Rating Curve= 0 ,0
Exp/Cntr(USF)=0,0
Exp/Cntr=0.3,0.1

Type RM Length L Ch R = 1 ,1758    ,705.1,695.2,676.4
XS GIS Cut Line= 4
1636394.26085918 445654.659927051636372.21152678445808.361247215
1636389.11727771446008.9249287671636392.19105061446090.379910546
#Sta/Elev= 30
       0  996.48      14   994.9    38.9  990.64    70.6  982.51    78.7  978.65
    86.8  973.76    94.8  966.92     107  953.39     115  947.19   119.1  945.03
   139.3  943.64   147.4  941.34   167.5  940.08   203.6  938.16   219.7  938.28
   255.8  935.61   263.8  936.53   275.9  936.57   292.3  934.42     304  933.44
     316  933.52     320  934.33     324  936.71   336.1  937.12   340.1  938.54
   348.1  943.09   372.2  946.91   412.2  957.56   432.1  969.43   438.1   973.9
#Mann= 5 ,-1,0
       0      .1       0      30     .06       0     130      .1       0
   292.3    .045       0     320      .1       0
Bank Sta=292.3,320
XS Rating Curve= 0 ,0
Exp/Cntr(USF)=0,0
Exp/Cntr=0.3,0.1

Type RM Length L Ch R = 1 ,1063    ,661.4,650,634.3
XS GIS Cut Line= 3
1635632.61528382446188.8352134191636092.43104011 446414.40520707
1636195.09430645446415.851168568
#Sta/Elev= 30
       0   942.8   277.4  933.99   289.3  933.07     298  929.91   302.4  929.16
   315.8  928.98   324.7  930.08   333.6  931.48   355.9  931.56   364.8  935.31
   378.1  939.52   400.4  944.26   409.3  947.26   429.8  960.05     445  967.25
   453.9  973.76   458.3  978.19   462.8  981.63   480.6   987.1     494  989.79
   507.4  995.72   527.8 1010.11   535.8 1016.99   563.9  1036.9   571.9 1040.98
   583.9 1044.89   587.9 1047.07   599.9 1059.08   603.9 1061.67   614.8 1066.04
#Mann= 4 ,-1,0
       0     .05       0     260      .1       0     298    .045       0
   324.7      .1       0
Bank Sta=298,324.7
XS Rating Curve= 0 ,0
Exp/Cntr(USF)=0,0
Exp/Cntr=0.3,0.1

Type RM Length L Ch R = 1 ,412     ,354.1,355.7,354.1
XS GIS Cut Line= 4
1635602.81401735446942.3835883651635986.97706808 446819.40456298
1636116.98346634446821.7470206061636197.79825445446844.000368057
#Sta/Elev= 30
       0  994.16      28  982.16    34.3  978.47    58.5  955.21    68.6  946.82
    81.2  944.14      98  936.94   114.8  936.55   127.4   933.6   139.3  927.63
   165.2  926.21   175.1 927.615     182  929.51   196.6  930.86   240.8  930.81
   303.8  933.31   362.6  934.04   412.5  936.33   432.5   938.9   456.5  947.35
   476.3  961.58   492.1  969.77   500.5  975.68   512.5  978.94   524.5  987.54
     574 1004.92   586.4 1008.27   594.7 1012.51   611.3 1024.26   617.2 1027.38
#Mann= 3 ,-1,0
       0      .1       0   139.3    .045       0   175.1      .1       0
Bank Sta=139.3,175.1
XS Rating Curve= 0 ,0
Exp/Cntr(USF)=0,0
Exp/Cntr=0.3,0.1

Type RM Length L Ch R = 1 ,57      ,,,
XS GIS Cut Line= 3
1635707.05855863447266.7898702611636128.35104439447152.541060561
1636222.96333993447127.549133439
#Sta/Elev= 30
       0  959.09    13.5  949.41    23.9  944.98    38.4   940.7    59.1  935.83
    75.7   935.3    79.8  934.36    88.1  930.83   100.6  929.64   108.9  927.65
   146.2  925.25   166.9     925   187.6     924   195.1  925.02   204.2  929.26
   303.6  929.97   324.4  930.96   349.2  934.08   374.1  938.84   386.5  942.65
   403.1  950.92   415.5  959.64     428   966.6   449.4  981.17     457  983.85
   473.5  986.72   485.9  989.82   510.7  998.38   527.3 1005.71   534.4 1009.73
#Mann= 3 ,-1,0
       0      .1       0   166.9    .045       0   195.1      .1       0
Bank Sta=166.9,195.1
XS Rating Curve= 0 ,0
Exp/Cntr(USF)=0,0
Exp/Cntr=0.3,0.1
LCMann Table=0

Chan Stop Cuts=-1
Use User Specified Reach Order=0
Composite Channel Slope=5